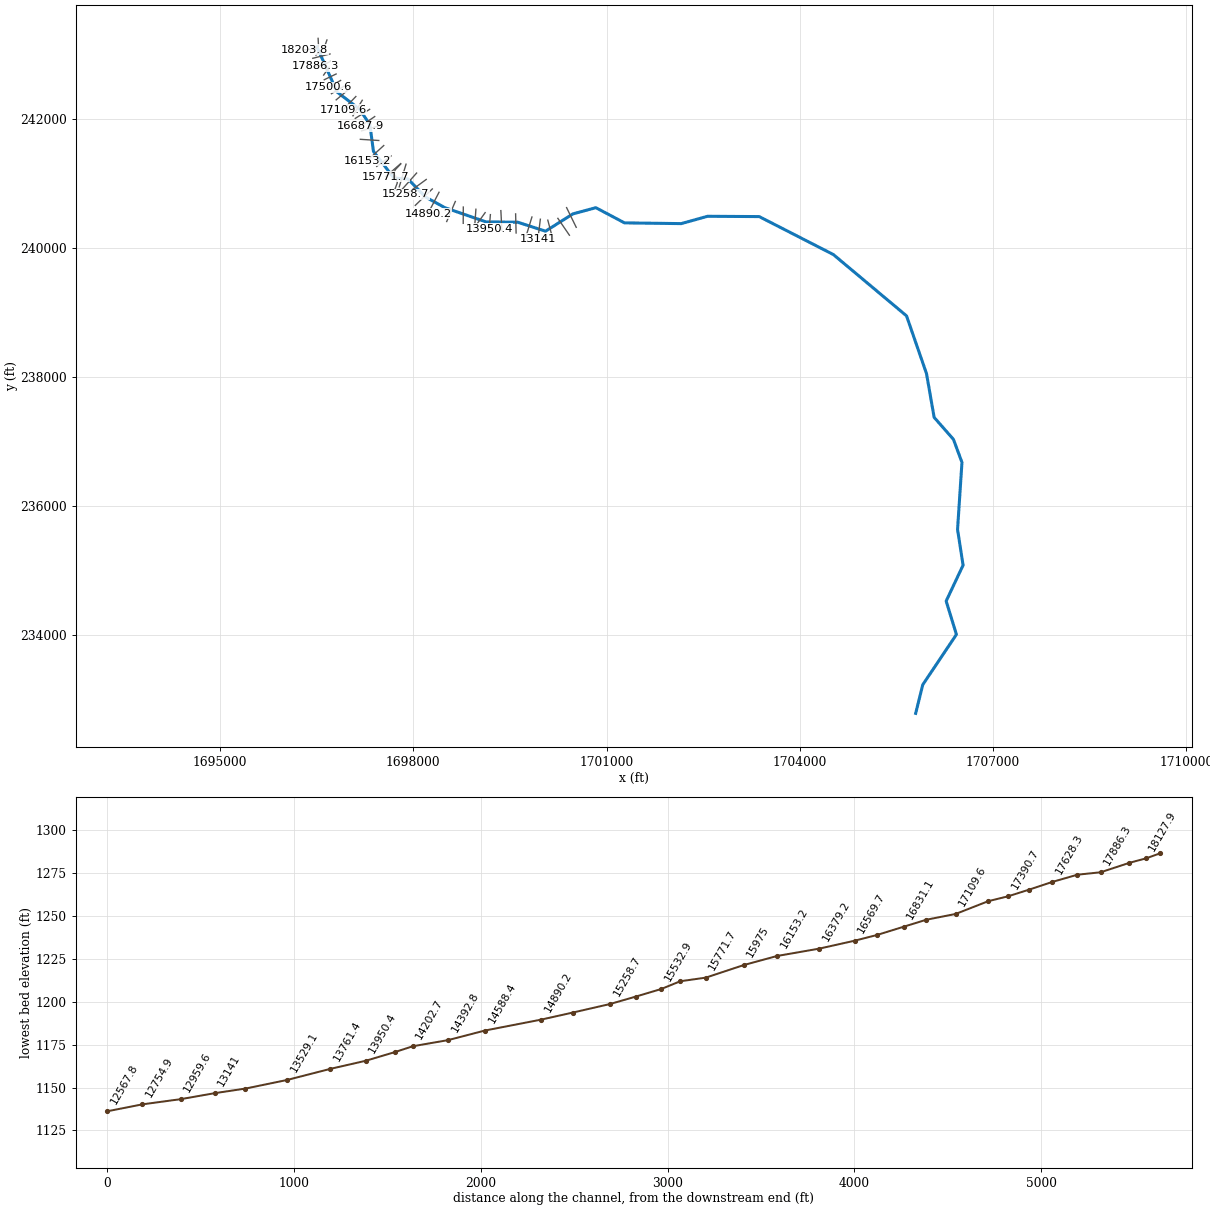
--- brwnngfrk.prj (project) ---

Proj Title=brwnngfrk
Current Plan=p01
Default Exp/Contr=0,0
English Units
Geom File=g01
Flow File=f01
Plan File=p01
BEGIN DESCRIPTION:
END DESCRIPTION:
DSS Export Rating Curves= 0
DSS Export Rating Curve Sorted= 0
DSS Export Volume Flow Curves= 0
DXF OffsetX= 0
DXF OffsetY= 0
DXF ScaleX= 0
DXF ScaleY= 0

--- brwnngfrk.p01 (plan) ---

Plan Title=Floodplain
Program Version=4.00
Geom File=g01
Flow File=f01
K Sum by GR=0
Std Step Tol=0.01
Critical Tol=0.01
Num of Std Step Trials=20
Max Error Tol=0.3
Flow Tol Ratio=0.001
Split Flow NTrial=30
Split Flow Tol=0.02
Split Flow Ratio=0.02
Log Output Level=0
Friction Slope Method=1
Unsteady Friction Slope Method=2
Unsteady Bridges Friction Slope Method=1
Global Log Level=0
CheckData=False
Run HTab=0
Run UNet=0
Run PostProcess=0
UNET Theta=0
UNET Theta Warmup=0
UNET ZTol=0
UNET ZSATol=0
UNET MxIter=0
UNET MaxInSteps=0
UNET DtIC=0
UNET DtMin=0
UNET MaxCRTS=0
UNET WFStab=0
UNET SFStab=0
UNET WFX=0
UNET SFX=0
UNET DSS MLevel=0
UNET DZMax Abort=0
UNET Convert EG Bridges=0
UNET Use Existing IB Tables=0
UNET Froude Limit=0
UNET Froude Power=0
Write IC File=0
Echo Input=False
Echo Output=False
Write Detailed=0

--- brwnngfrk.f01 (steady flow) ---

Flow Title=NFF Regression Equation
Program Version=4.00
Number of Profiles= 1
Profile Names=P100yr
River Rch & RM=brwnngfrk,Main            ,18203.8
     266
River Rch & RM=brwnngfrk,Main            ,18040.2
     435
River Rch & RM=brwnngfrk,Main            ,16831.1
     472
River Rch & RM=brwnngfrk,Main            ,16569.7
     519
River Rch & RM=brwnngfrk,Main            ,15258.7
     563
River Rch & RM=brwnngfrk,Main            ,13761.4
     622
River Rch & RM=brwnngfrk,Main            ,12259.2
     689
River Rch & RM=brwnngfrk,Main            ,9283.6
     761
River Rch & RM=brwnngfrk,Main            ,8968.7
    1024
River Rch & RM=brwnngfrk,Main            ,8246.3
    1034
River Rch & RM=brwnngfrk,Main            ,6537.2
    1146
River Rch & RM=brwnngfrk,Main            ,4497.2
    1244
River Rch & RM=brwnngfrk,Main            ,91.3
    1377
Boundary for River Rch & Prof#=brwnngfrk,Main            , 1
Up Type= 0
Dn Type= 3
Dn Slope=0.017367
DSS Import GetInterval= 0
DSS Import GetPeak= 0
DSS Import FillOption= 0

--- brwnngfrk.g01 (geometry) ---

Geom Title=USGS 10m DEM
Program Version=4.00

River Reach=brwnngfrk       ,Main
Reach XY= 30
       1696504.7      243122.725     1696815.524      242423.098
     1697162.831        242157.7     1697325.889      241917.549
     1697382.157      241498.944     1697700.432      241085.144
     1697918.492      241071.162     1698189.876      240791.405
     1698491.584      240625.988     1699128.008      240405.811
     1699621.046      240400.561     1700053.144      240261.203
      1700478.89      240529.999     1700834.181      240625.894
     1701279.493      240390.157     1702159.904      240378.716
     1702568.316      240492.481     1703370.169      240487.842
     1704521.428       239898.58     1705657.245      238946.609
      1705967.49      238049.756     1706085.831      237370.697
     1706384.848       237030.32     1706517.654      236672.888
     1706449.237      235631.525     1706535.117      235075.668
     1706272.457       234519.37      1706431.81       234001.01
     1705909.019      233219.926     1705799.038      232775.865

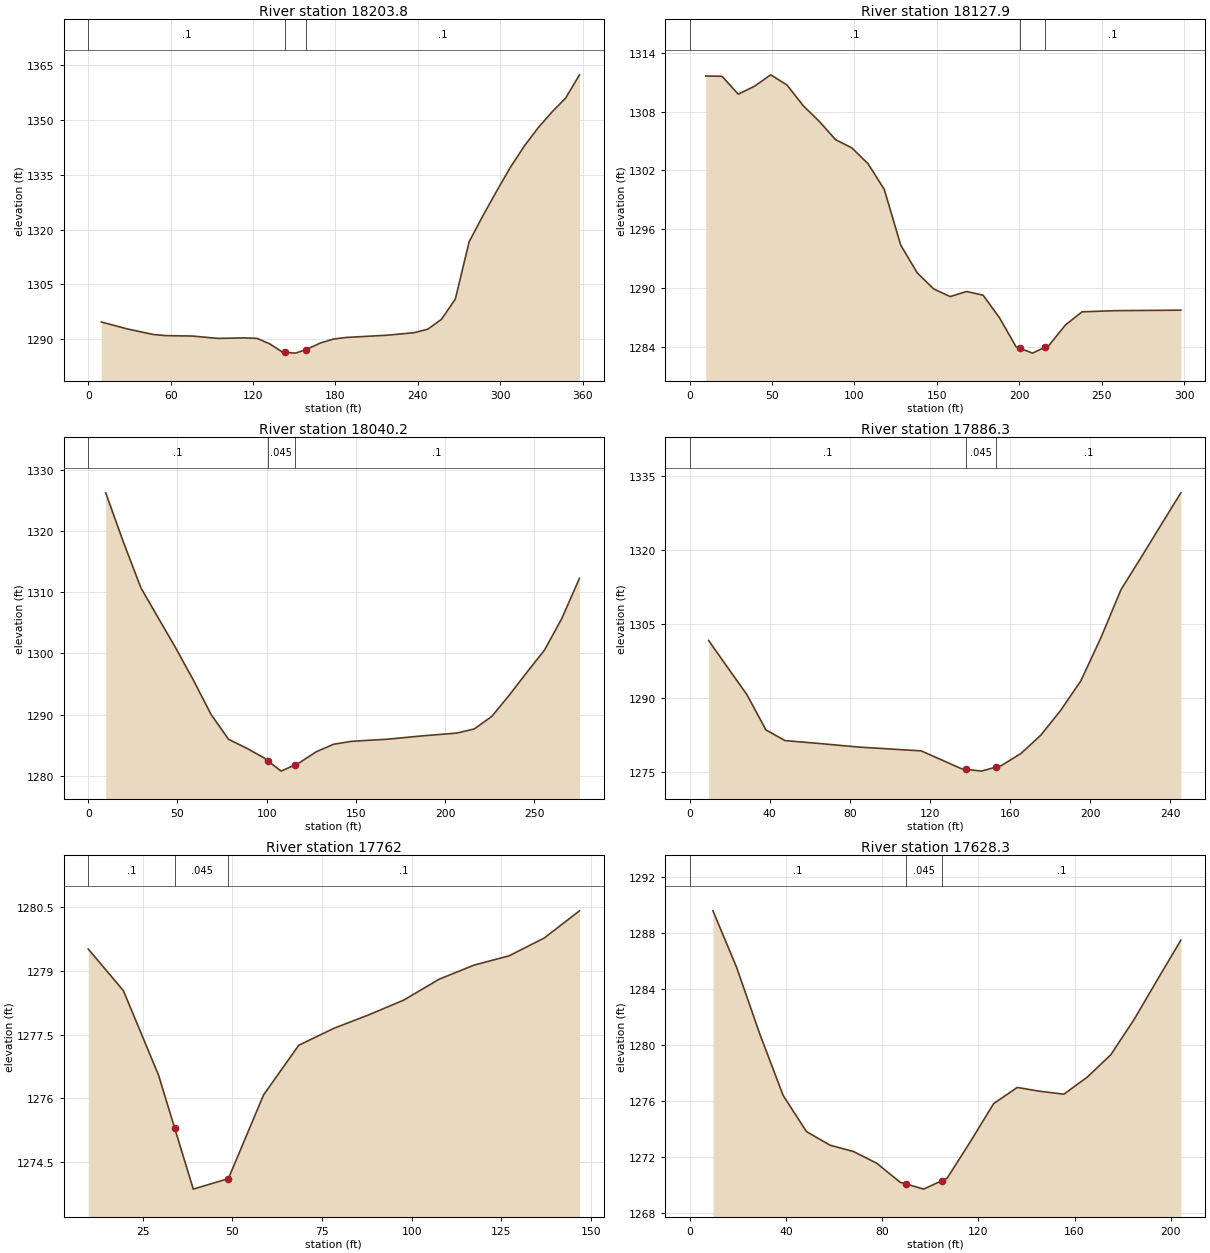
Type RM Length L Ch R = 1 ,18203.8 ,73.1,75.9,78.8
XS GIS Cut Line= 4
     1696522.823      243254.955     1696529.463      243132.091
     1696469.835      243088.334     1696309.469      243077.534
#Sta/Elev= 30
     9.5 1294.75    28.4 1292.86    47.3 1291.34    56.8 1291.02    75.7 1290.92
    94.6 1290.27   113.6 1290.41     123 1290.27   132.3 1288.76   141.5  1286.5
   143.3 1286.45   150.8 1286.25   158.3 1287.16   169.3 1289.05   178.5 1290.08
   187.8 1290.53   217.1 1291.13   237.2 1291.82   247.2 1292.78   257.3  1295.5
   267.3 1300.99   277.4 1316.68   287.4 1323.75   297.5 1330.56   307.5 1337.04
   317.6 1342.82   327.6 1347.77   337.6 1352.05   347.7 1355.91   357.7 1362.24
#Mann= 3 , 0 , 0
       0      .1       0   143.3    .045       0   158.3      .1       0
Bank Sta=143.3,158.3
XS Rating Curve= 0 ,0
Exp/Cntr=0.3,0.1

Type RM Length L Ch R = 1 ,18127.9 ,99.3,87.7,76.1
XS GIS Cut Line= 3
     1696660.076      243229.809     1696620.409      243118.546
     1696489.796      242994.705
#Sta/Elev= 28
     9.8 1311.65    19.7 1311.62    29.5 1309.79    39.4 1310.61    49.2 1311.77
    59.1 1310.73    68.9 1308.62    78.7 1307.01    88.6 1305.14    98.4 1304.31
   108.3 1302.68   118.1 1300.07   128.1 1294.37   138.1 1291.54   148.1 1289.89
   158.1 1289.11   168.1 1289.63   178.1 1289.25   188.1 1286.93   198.1 1283.98
   200.6 1283.81   208.1 1283.33   215.6 1283.93   218.1 1284.13   228.1 1286.21
   238.1 1287.55   258.1 1287.67   298.1 1287.72
#Mann= 3 , 0 , 0
       0      .1       0   200.6    .045       0   215.6      .1       0
Bank Sta=200.6,215.6
XS Rating Curve= 0 ,0
Exp/Cntr=0.3,0.1

Type RM Length L Ch R = 1 ,18040.2 ,154.6,153.9,153.3
XS GIS Cut Line= 2
     1696707.484       243012.12     1696440.453      242945.362
#Sta/Elev= 30
     9.8 1326.22    19.7 1318.18    29.5 1310.72    39.3 1305.76    49.2 1300.79
      59 1295.58    68.8 1290.04    78.6 1285.97    88.5 1284.55    98.3 1282.97
   100.6 1282.45   108.1 1280.77   115.6 1281.76     118 1282.08   127.8 1283.94
   137.6 1285.17   147.5 1285.63   157.3 1285.81   167.1 1285.97   176.9 1286.24
   186.8 1286.52   196.6 1286.75   206.4 1286.98   216.3 1287.66   226.1 1289.71
   235.9 1293.18   245.8 1296.93   255.6 1300.53   265.4 1305.74   275.2 1312.26
#Mann= 3 , 0 , 0
       0      .1       0   100.6    .045       0   115.6      .1       0
Bank Sta=100.6,115.6
XS Rating Curve= 0 ,0
Exp/Cntr=0.3,0.1

Type RM Length L Ch R = 1 ,17886.3 ,107.4,124.3,141.3
XS GIS Cut Line= 3
     1696709.419       242896.02     1696633.954      242855.385
     1696478.186      242820.554
#Sta/Elev= 27
     9.5 1301.67      19 1296.21    28.6 1290.74    38.1 1283.61    47.6 1281.45
    57.1 1281.12    66.7 1280.79    76.2 1280.43    85.7  1280.1    95.7 1279.86
   105.7  1279.6   115.6 1279.37   125.6 1277.58   135.6 1275.78   138.1 1275.65
   145.6 1275.27   153.1 1276.09   155.5 1276.35   165.5 1278.85   175.5 1282.59
   185.5 1287.67   195.4 1293.55   205.4 1302.26   215.4 1311.95   225.4 1318.44
   235.3 1324.97   245.3 1331.53
#Mann= 3 , 0 , 0
       0      .1       0   138.1    .045       0   153.1      .1       0
Bank Sta=138.1,153.1
XS Rating Curve= 0 ,0
Exp/Cntr=0.3,0.1

Type RM Length L Ch R = 1 ,17762   ,145.7,133.7,121.8
XS GIS Cut Line= 2
     1696692.004      242806.042     1696608.798      242685.104
#Sta/Elev= 18
     9.8 1279.52    19.6 1278.54    29.4 1276.55    31.6 1275.94    33.91275.302
    39.1 1273.86    46.6 1274.05    48.9 1274.11    58.7 1276.08    68.5 1277.25
    78.3 1277.65    88.1 1277.97    97.9 1278.32   107.7 1278.81   117.4 1279.14
   127.2 1279.36     137 1279.78   146.8 1280.42
#Mann= 3 , 0 , 0
     9.8      .1       0    33.9    .045       0    48.9      .1       0
Bank Sta=33.9,48.9
XS Rating Curve= 0 ,0
Exp/Cntr=0.3,0.1

Type RM Length L Ch R = 1 ,17628.3 ,126.5,127.7,128.9
XS GIS Cut Line= 2
     1696802.299      242701.551     1696618.474      242612.541
#Sta/Elev= 23
     9.7 1289.58    19.5 1285.55    29.2 1280.76    38.9 1276.37    48.6 1273.79
    58.4 1272.82    68.1 1272.37    77.8 1271.53    87.5 1270.17    89.8 1270.06
    97.3 1269.68   104.8 1270.28     107 1270.45   116.7 1273.07   126.4  1275.8
   136.2 1276.95   145.9 1276.67   155.6 1276.47   165.3 1277.69   175.1 1279.29
   184.8 1281.82   194.5 1284.67   204.2 1287.48
#Mann= 3 , 0 , 0
       0      .1       0    89.8    .045       0   104.8      .1       0
Bank Sta=89.8,104.8
XS Rating Curve= 0 ,0
Exp/Cntr=0.3,0.1

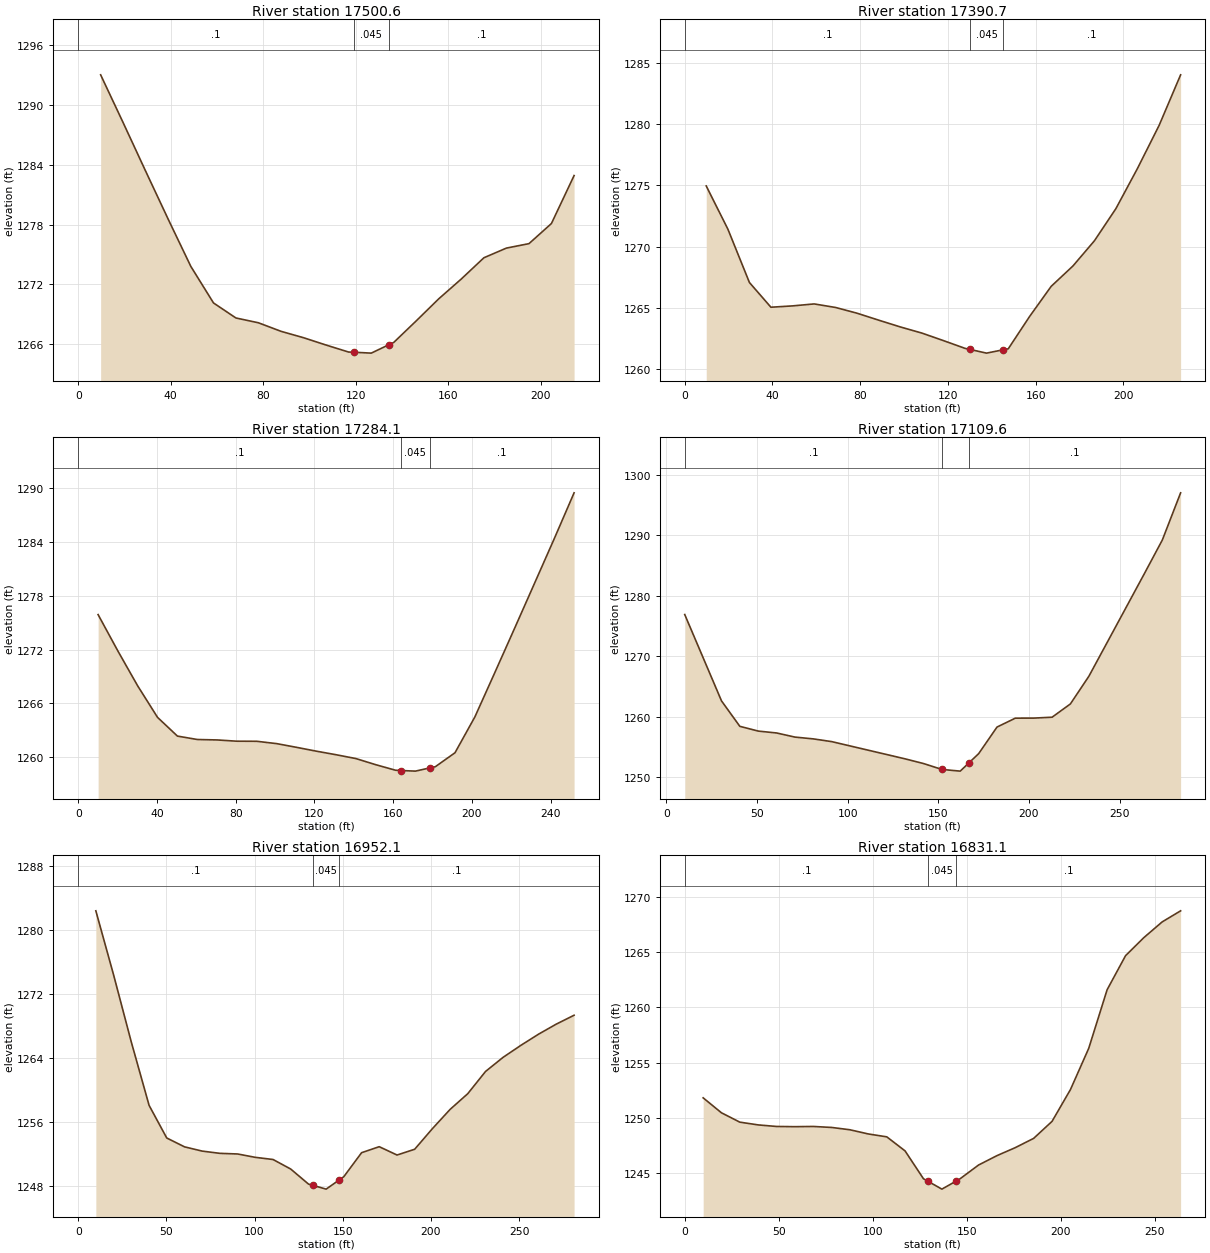
Type RM Length L Ch R = 1 ,17500.6 ,109.1,109.9,110.6
XS GIS Cut Line= 2
      1696871.96      242600.931     1696684.264      242497.408
#Sta/Elev= 24
     9.7 1293.04    19.5  1288.2    29.2 1283.34      39 1278.49    48.7 1273.79
    58.5 1270.12    68.2 1268.61    77.9 1268.13    87.7 1267.27    97.4 1266.63
   107.2 1265.89   116.9 1265.19   119.2 1265.17   126.7 1265.08   134.2 1265.91
   136.4 1266.15   146.1 1268.31   155.9 1270.54   165.6 1272.52   175.4 1274.66
   185.1 1275.63   194.9 1276.08   204.6  1278.1   214.4 1282.92
#Mann= 3 , 0 , 0
       0      .1       0   119.2    .045       0   134.2      .1       0
Bank Sta=119.2,134.2
XS Rating Curve= 0 ,0
Exp/Cntr=0.3,0.1

Type RM Length L Ch R = 1 ,17390.7 ,103,106.6,110.2
XS GIS Cut Line= 2
     1696923.909      242510.807     1696729.541      242395.284
#Sta/Elev= 25
     9.8 1274.95    19.7 1271.41    29.5 1267.06    39.3 1265.04    49.2 1265.15
      59 1265.31    68.8 1265.02    78.6 1264.55    88.5 1263.98    98.3 1263.43
   108.1 1262.93     118 1262.31   127.8 1261.68   130.1 1261.59   137.6 1261.29
   145.1 1261.56   147.5 1261.64   157.3  1264.3   167.1 1266.75     177 1268.41
   186.8 1270.47   196.6  1273.1   206.4 1276.37   216.3  1279.9   226.1 1284.03
#Mann= 3 , 0 , 0
       0      .1       0   130.1    .045       0   145.1      .1       0
Bank Sta=130.1,145.1
XS Rating Curve= 0 ,0
Exp/Cntr=0.3,0.1

Type RM Length L Ch R = 1 ,17284.1 ,172.2,174.6,177
XS GIS Cut Line= 2
     1696996.445      242461.288     1696802.944      242300.037
#Sta/Elev= 27
    10.1 1275.91    20.2 1271.83    30.2 1267.96    40.3 1264.44    50.4 1262.35
    60.5 1261.97    70.5 1261.92    80.6 1261.78    90.7 1261.77   100.8 1261.51
   110.8  1261.1   120.9 1260.67     131 1260.27   141.1 1259.84   151.1 1259.16
   161.2 1258.54   163.8 1258.51   171.3 1258.44   178.8 1258.81   181.4 1258.93
   191.4 1260.49   201.5 1264.49   211.6 1269.42   221.7 1274.39   231.7 1279.35
   241.8 1284.37   251.9  1289.5
#Mann= 3 , 0 , 0
       0      .1       0   163.8    .045       0   178.8      .1       0
Bank Sta=163.8,178.8
XS Rating Curve= 0 ,0
Exp/Cntr=0.3,0.1

Type RM Length L Ch R = 1 ,17109.6 ,152.5,157.5,162.5
XS GIS Cut Line= 2
     1697108.676      242351.638     1696911.305      242147.816
#Sta/Elev= 23
    10.1 1276.91    30.4 1262.62    40.5 1258.42    50.7 1257.63    60.8 1257.32
    70.9 1256.64    81.1 1256.34    91.2 1255.89   131.7 1253.04   141.9 1252.26
     152 1251.29   162.1 1251.01     1671252.402   172.3 1253.91   182.4  1258.3
   192.5 1259.77   202.7 1259.78   212.8 1259.93   222.9 1262.13   233.1 1266.71
   263.5 1283.56   273.6 1289.23   283.7 1297.04
#Mann= 3 , 0 , 0
    10.1      .1       0     152    .045       0     167      .1       0
Bank Sta=152,167
XS Rating Curve= 0 ,0
Exp/Cntr=0.3,0.1

Type RM Length L Ch R = 1 ,16952.1 ,131.5,121,110.5
XS GIS Cut Line= 2
     1697208.006      242293.587     1697063.526      242052.356
#Sta/Elev= 30
      10 1282.39    20.1 1274.36    30.1 1266.01    40.2 1258.09    50.2 1254.02
    60.3 1252.91    70.3 1252.38    80.3  1252.1    90.4 1252.02   100.4  1251.6
   110.5 1251.33   120.5 1250.14   130.6 1248.26   133.1  1248.1   140.6 1247.63
   148.1 1248.79   150.6 1249.18   160.7 1252.18   170.7 1252.93   180.8 1251.89
   190.8 1252.61   200.8 1255.17   210.9 1257.59   220.9 1259.55     231 1262.33
     241  1264.1   251.1  1265.6   261.1 1266.99   271.1 1268.24   281.2 1269.35
#Mann= 3 , 0 , 0
       0      .1       0   133.1    .045       0   148.1      .1       0
Bank Sta=133.1,148.1
XS Rating Curve= 0 ,0
Exp/Cntr=0.3,0.1

Type RM Length L Ch R = 1 ,16831.1 ,142.2,143.2,144.2
XS GIS Cut Line= 2
     1697322.817      242152.977     1697099.646      242012.366
#Sta/Elev= 29
     9.8 1251.82    19.5 1250.47    29.3 1249.62    39.1 1249.37    48.8 1249.23
    58.6 1249.21    68.4 1249.23    78.2 1249.14    87.9 1248.93    97.7 1248.55
   107.5 1248.29   117.2 1247.02     127  1244.5   129.3 1244.28   136.8 1243.56
   144.3 1244.28   146.5  1244.5   156.3 1245.74   166.1 1246.59   175.8 1247.31
   185.6 1248.15   195.4 1249.69   205.2 1252.57   214.9 1256.29   224.7  1261.6
   234.5 1264.68   244.2 1266.31     254 1267.74   263.8 1268.74
#Mann= 3 , 0 , 0
       0      .1       0   129.3    .045       0   144.3      .1       0
Bank Sta=129.3,144.3
XS Rating Curve= 0 ,0
Exp/Cntr=0.3,0.1

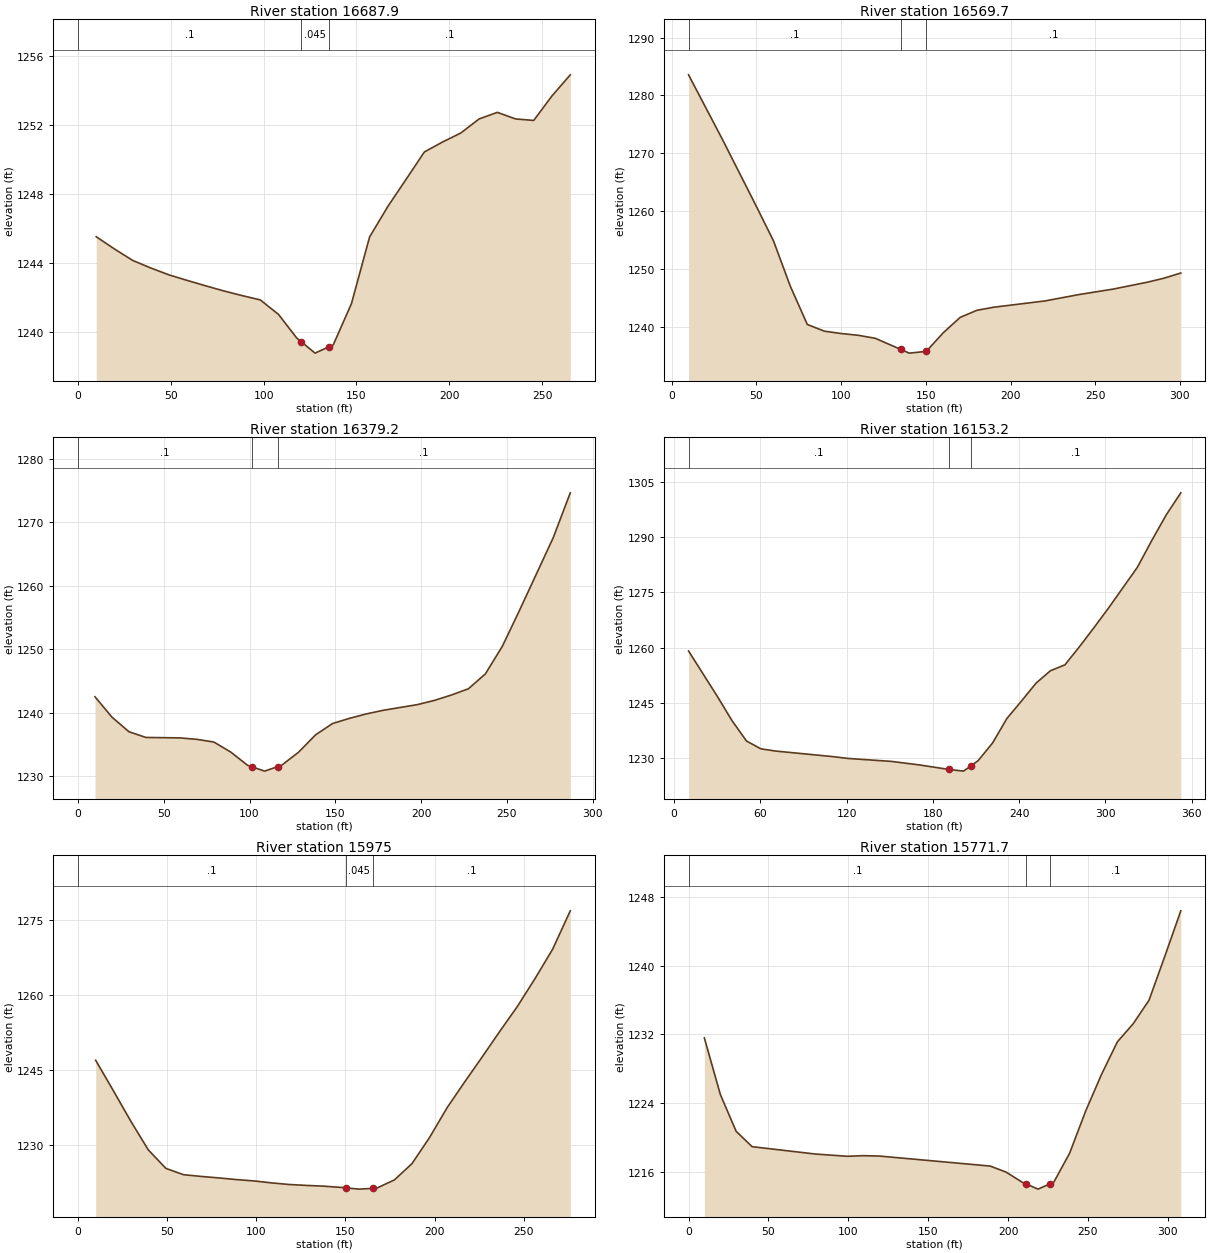
Type RM Length L Ch R = 1 ,16687.9 ,125.6,118.2,110.8
XS GIS Cut Line= 2
     1697401.507      242040.746     1697183.496      241889.815
#Sta/Elev= 29
     9.8 1245.51    19.6  1244.8    29.5 1244.13    39.3 1243.69    49.1 1243.29
    58.9 1242.97    68.7 1242.66    78.6 1242.36    88.4 1242.09    98.2 1241.84
     108    1241   117.8 1239.63   120.2 1239.42   127.7 1238.75   135.2 1239.12
   137.5 1239.23   147.3 1241.62   157.1  1245.5     167 1247.28   176.8 1248.85
   186.6 1250.43   196.4 1251.01   206.2 1251.53   216.1 1252.35   225.9 1252.73
   235.7 1252.35   245.5 1252.26   255.3 1253.68   265.2 1254.91
#Mann= 3 , 0 , 0
       0      .1       0   120.2    .045       0   135.2      .1       0
Bank Sta=120.2,135.2
XS Rating Curve= 0 ,0
Exp/Cntr=0.3,0.1

Type RM Length L Ch R = 1 ,16569.7 ,198.2,190.5,182.8
XS GIS Cut Line= 2
     1697486.647      241901.425     1697197.686      241818.865
#Sta/Elev= 23
      10 1283.55    30.1 1272.33    50.1 1260.77    60.1 1254.88    70.1 1246.99
    80.1 1240.41    90.2 1239.25   100.2 1238.84   110.2 1238.54   120.2 1238.02
   135.31236.094   140.2 1235.46   150.3 1235.76   160.3 1238.98   170.3 1241.64
   180.3 1242.87   190.3  1243.4   220.4 1244.48   240.4 1245.58   260.5 1246.52
   280.5  1247.7   290.5  1248.4   300.5  1249.3
#Mann= 3 , 0 , 0
      10      .1       0   135.3    .045       0   150.3      .1       0
Bank Sta=135.3,150.3
XS Rating Curve= 0 ,0
Exp/Cntr=0.3,0.1

Type RM Length L Ch R = 1 ,16379.2 ,207.2,225.9,244.7
XS GIS Cut Line= 2
     1697464.717      241669.224     1697178.336      241687.284
#Sta/Elev= 28
     9.9 1242.53    19.8 1239.32    29.7 1237.03    39.6 1236.13    59.4 1236.06
    69.3 1235.83    79.2 1235.41    89.1 1233.82    98.9 1231.74   101.3 1231.52
   108.8 1230.83   116.3 1231.53   118.7 1231.75   128.6 1233.81   138.5 1236.54
   148.4 1238.32   158.3 1239.14   168.2 1239.84   178.1 1240.41   197.9  1241.3
   207.8 1241.96   217.7 1242.81   227.6 1243.79   237.5 1246.13   247.4 1250.48
   257.3 1256.07   277.1 1267.59     287 1274.63
#Mann= 3 , 0 , 0
       0      .1       0   101.3    .045       0   116.3      .1       0
Bank Sta=101.3,116.3
XS Rating Curve= 0 ,0
Exp/Cntr=0.3,0.1

Type RM Length L Ch R = 1 ,16153.2 ,180.7,178.2,175.7
XS GIS Cut Line= 2
     1697541.904      241590.841     1697281.323       241353.48
#Sta/Elev= 27
    10.1 1259.12    30.2 1246.77    40.3 1240.26    50.4 1234.72    60.4  1232.6
    70.5    1232   110.8 1230.47   120.9 1229.99   151.1 1229.19   171.2  1228.2
   191.3    1227   201.4 1226.55   206.31227.922   211.5 1229.38   221.6  1234.2
   231.6 1240.86   241.7 1245.56   251.8  1250.4   261.8 1253.77   271.9 1255.37
     282 1260.28   292.1 1265.45   302.1  1270.7   322.3 1281.82   332.3 1289.07
   342.4 1296.05   352.5 1302.01
#Mann= 3 , 0 , 0
    10.1      .1       0   191.3    .045       0   206.3      .1       0
Bank Sta=191.3,206.3
XS Rating Curve= 0 ,0
Exp/Cntr=0.3,0.1

Type RM Length L Ch R = 1 ,15975   ,201.4,203.4,205.4
XS GIS Cut Line= 2
     1697655.638      241429.283     1697432.467      241266.743
#Sta/Elev= 30
     9.9 1247.02    19.7 1241.01    29.6 1234.85    39.4 1229.12    49.3 1225.41
    59.2 1224.15      69 1223.81    78.9 1223.51    88.7 1223.18    98.6 1222.91
   108.5 1222.52   118.3  1222.2   128.2 1222.01     138 1221.86   147.9  1221.6
   150.3 1221.52   157.8 1221.27   165.3 1221.43   167.6 1221.47   177.5 1223.12
   187.3 1226.36   197.2  1231.6   207.1 1237.59   216.9  1242.7   226.8 1247.74
   236.6 1252.81   246.5 1257.81   256.4 1263.38   266.2  1269.2   276.1 1276.88
#Mann= 3 , 0 , 0
       0      .1       0   150.3    .045       0   165.3      .1       0
Bank Sta=150.3,165.3
XS Rating Curve= 0 ,0
Exp/Cntr=0.3,0.1

Type RM Length L Ch R = 1 ,15771.7 ,110.6,136.8,162.9
XS GIS Cut Line= 2
     1697805.279      241310.603     1697573.078      241108.072
#Sta/Elev= 23
     9.9 1231.58    19.9 1224.99    29.8 1220.69    39.8  1218.9    79.5 1218.04
    99.4 1217.78   109.3 1217.85   119.3 1217.81   188.8 1216.64   198.8 1215.93
   208.7 1214.77   211.2 1214.57   218.7 1213.95   226.2 1214.56   228.6 1214.76
   238.5 1218.13   248.5 1223.03   258.4  1227.3   268.4 1231.13   278.3 1233.24
   288.2 1235.98   298.2 1241.16   308.1 1246.41
#Mann= 3 , 0 , 0
       0      .1       0   211.2    .045       0   226.2      .1       0
Bank Sta=211.2,226.2
XS Rating Curve= 0 ,0
Exp/Cntr=0.3,0.1

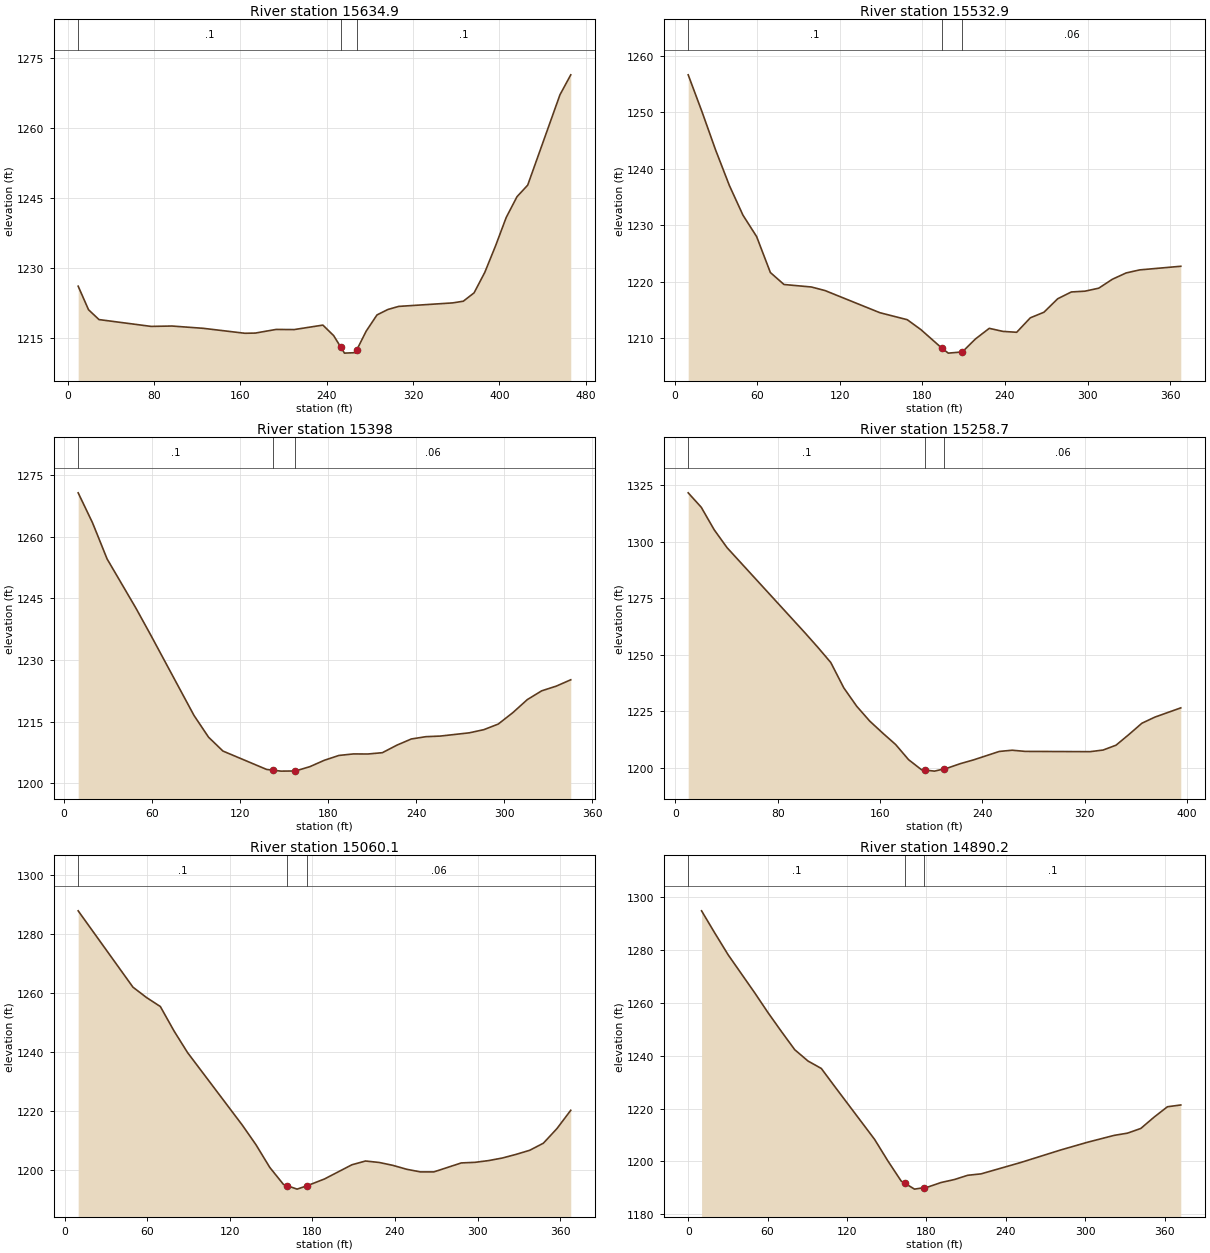
Type RM Length L Ch R = 1 ,15634.9 ,115.4,102,88.7
XS GIS Cut Line= 6
     1697803.989      241302.863     1697717.317      241212.007
      1697704.07      241145.767     1697724.344      241119.296
     1697752.389      241012.611     1697707.238      240891.351
#Sta/Elev= 30
     9.7 1226.17    19.3 1221.13      29 1219.02    77.3 1217.56    96.6 1217.64
   125.6 1217.15   164.2 1216.09   173.8 1216.13   193.1 1216.91   209.8 1216.88
   236.5 1217.84   246.5 1215.58     2531213.147   256.5 1211.84   266.6 1211.94
     2681212.584   276.6 1216.54   286.6 1220.01   296.7 1221.18   306.7 1221.84
   356.7 1222.59   366.6 1222.95   376.6 1224.74   386.5 1229.11   396.5  1234.8
   406.4 1240.89   416.4 1245.33   426.3  1247.8   456.2 1267.14   466.2 1271.41
#Mann= 3 , 0 , 0
     9.7      .1       0     253    .045       0     268      .1       0
Bank Sta=253,268
XS Rating Curve= 0 ,0
Exp/Cntr=0.3,0.1

Type RM Length L Ch R = 1 ,15532.9 ,144.7,134.9,125
XS GIS Cut Line= 2
     1697887.839      241301.573     1697782.059      240949.401
#Sta/Elev= 30
     9.9  1256.6    19.9 1250.08    29.8  1243.3    39.8 1237.01    49.7 1231.74
    59.6 1227.96    69.6 1221.59    79.5 1219.47    99.4 1219.03   109.3  1218.4
   149.1 1214.48     169 1213.24   178.9 1211.49     1941208.235   198.8 1207.32
     2091207.532   218.6 1209.84   228.6 1211.71   238.5 1211.17   248.5 1211.01
   258.4 1213.57   268.3 1214.56   278.3 1216.95   288.2 1218.15   298.1 1218.29
   308.1 1218.82     318  1220.4     328 1221.52   337.9 1222.06   367.7  1222.7
#Mann= 3 , 0 , 0
     9.9      .1       0     194    .045       0     209     .06       0
Bank Sta=194,209
XS Rating Curve= 0 ,0
Exp/Cntr=0.3,0.1

Type RM Length L Ch R = 1 ,15398   ,144.1,139.3,134.6
XS GIS Cut Line= 2
      1698051.67      241163.542     1697822.049      240905.541
#Sta/Elev= 30
     9.9 1270.74    19.7 1263.43    29.6 1254.64    49.3 1242.61    59.2 1236.18
    88.8 1216.51    98.7 1211.22   108.5 1207.84   138.2 1203.37   142.91203.168
     148 1202.95   157.9 1202.99   167.8 1204.05   177.6  1205.6   187.5 1206.77
   197.4 1207.14   207.2 1207.12   217.1 1207.44     227 1209.28   236.8 1210.78
   246.7 1211.34   256.6 1211.49   276.3 1212.28   286.2 1213.05     296 1214.41
   305.9 1217.18   315.8 1220.37   325.6 1222.51   335.5 1223.65   345.4  1225.2
#Mann= 3 , 0 , 0
     9.9      .1       0   142.9    .045       0   157.9     .06       0
Bank Sta=142.9,157.9
XS Rating Curve= 0 ,0
Exp/Cntr=0.3,0.1

Type RM Length L Ch R = 1 ,15258.7 ,195.5,198.5,201.6
XS GIS Cut Line= 2
     1698201.311      241064.212     1697882.679      240830.721
#Sta/Elev= 30
    10.1 1321.73    20.3 1315.34    30.4 1305.39    40.5 1297.44   101.3 1259.82
   111.4 1253.38   121.5 1246.66   131.7 1235.42   141.8 1227.28   151.9 1220.76
   162.1 1215.42   172.2 1210.36   182.3 1203.66   192.4 1199.21   195.1 1199.05
   202.6 1198.59   210.1 1199.59   212.7 1199.93   222.8 1201.91     233 1203.55
   253.2  1207.3   263.3 1207.84   273.5 1207.32   324.1  1207.2   334.3 1207.92
   344.4 1210.06   354.5 1214.81   364.6 1219.78   374.8  1222.5     395 1226.58
#Mann= 3 , 0 , 0
    10.1      .1       0   195.1    .045       0   210.1     .06       0
Bank Sta=195.1,210.1
XS Rating Curve= 0 ,0
Exp/Cntr=0.3,0.1

Type RM Length L Ch R = 1 ,15060.1 ,162.6,169.9,177.2
XS GIS Cut Line= 2
     1698295.481      240917.151      1698031.03       240661.73
#Sta/Elev= 30
     9.9 1287.76    49.7 1261.94    59.6 1258.42    69.6 1255.39    79.5 1247.15
    89.4 1239.79   129.2 1215.24   139.1 1208.62   149.1 1200.97     159 1195.24
   161.4 1194.85   168.9 1193.64   176.4 1194.82   188.8 1197.07   208.7 1201.87
   218.6 1203.15   228.5 1202.66   238.5 1201.68   248.4 1200.37   258.4 1199.47
   268.3 1199.47   288.2  1202.5   298.1  1202.7     308 1203.29     318 1204.16
   327.9 1205.38   337.9 1206.78   347.8 1209.17   357.7 1214.13   367.7 1220.31
#Mann= 3 , 0 , 0
     9.9      .1       0   161.4    .045       0   176.4     .06       0
Bank Sta=161.4,176.4
XS Rating Curve= 0 ,0
Exp/Cntr=0.3,0.1

Type RM Length L Ch R = 1 ,14890.2 ,300.2,301.8,303.5
XS GIS Cut Line= 2
     1698399.971      240865.551     1698228.401      240535.309
#Sta/Elev= 30
    10.1 1294.91    20.1  1286.5    30.2 1278.25    50.3 1263.83    60.3 1256.36
    70.4 1249.24    80.5 1242.32    90.5 1238.04   100.6 1235.21   110.6 1228.47
   140.8 1208.39   150.9 1200.19   160.9  1192.6   163.5 1191.81     171 1189.52
   178.5  1190.1     181 1190.29   191.1 1192.03   201.2 1193.16   211.2 1194.76
   221.3  1195.3   251.5 1199.64   281.6 1204.37   301.7 1207.27   321.9 1209.88
   331.9 1210.71     342  1212.5     352 1216.77   362.1 1220.71   372.2 1221.39
#Mann= 3 , 0 , 0
       0      .1       0   163.5    .045       0   178.5      .1       0
Bank Sta=163.5,178.5
XS Rating Curve= 0 ,0
Exp/Cntr=0.3,0.1

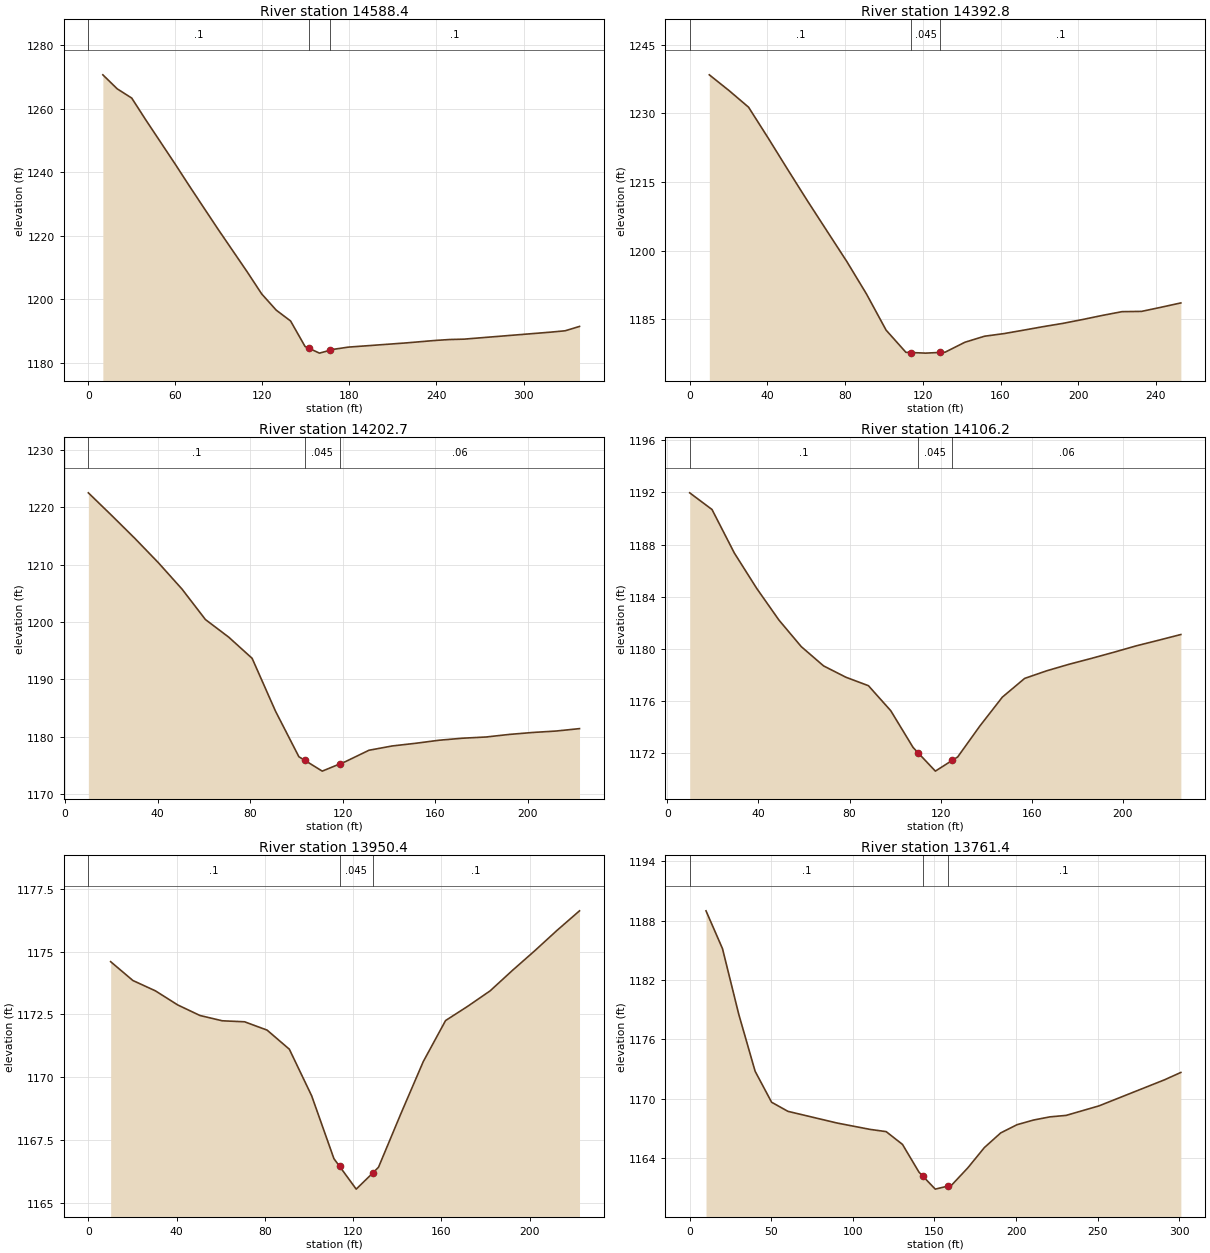
Type RM Length L Ch R = 1 ,14588.4 ,186.5,195.6,204.8
XS GIS Cut Line= 2
     1698652.813       240722.36     1698519.065      240411.282
#Sta/Elev= 25
      10 1270.58    19.9 1266.18    29.9 1263.28    39.8 1256.28    59.8 1242.58
    69.7 1235.63    79.7 1228.75    89.6 1221.96   109.6 1208.62   119.5 1201.75
   129.5 1196.66   139.4 1193.26   149.4 1185.24   151.8 1184.73   159.3 1183.15
   166.8 1184.07   169.3 1184.37   179.3 1185.04   219.1 1186.36     239 1187.13
     249 1187.42   258.9 1187.54   318.7 1189.74   328.7 1190.17   338.6 1191.54
#Mann= 3 , 0 , 0
       0      .1       0   151.8    .045       0   166.8      .1       0
Bank Sta=151.8,166.8
XS Rating Curve= 0 ,0
Exp/Cntr=0.3,0.1

Type RM Length L Ch R = 1 ,14392.8 ,191.7,190.1,188.6
XS GIS Cut Line= 2
     1698776.653       240635.93     1698775.363      240383.089
#Sta/Elev= 27
    10.1 1238.43    20.2 1235.01    30.3 1231.36    40.5 1224.55    50.6 1217.64
    60.7 1210.84    70.8 1204.22    80.9 1197.62      91 1190.54   101.1 1182.64
   111.3 1177.79   113.9 1177.75   121.4 1177.62   128.9 1177.77   131.5 1177.83
   141.6 1179.99   151.7 1181.31   161.8 1181.89   171.9 1182.64     182 1183.41
   192.2 1184.13   202.3 1184.97   212.4 1185.86   222.5 1186.68   232.6 1186.74
   242.7 1187.65   252.8 1188.59
#Mann= 3 , 0 , 0
       0      .1       0   113.9    .045       0   128.9      .1       0
Bank Sta=113.9,128.9
XS Rating Curve= 0 ,0
Exp/Cntr=0.3,0.1

Type RM Length L Ch R = 1 ,14202.7 ,108.9,96.4,83.9
XS GIS Cut Line= 2
     1698972.213      240601.768     1698956.733      240379.887
#Sta/Elev= 24
    10.1 1222.54    20.2 1218.59    30.3 1214.56    40.4 1210.34    50.6 1205.75
    60.7 1200.45    70.8 1197.37    80.9 1193.68      91 1184.47   101.1 1176.53
   103.7 1175.89   111.2 1174.02   118.7 1175.26   121.3 1175.69   131.4 1177.66
   141.5 1178.41   151.7 1178.88   161.8 1179.41   171.9 1179.76     182 1179.97
   192.1 1180.42   202.2 1180.76   212.3 1181.01   222.4 1181.43
#Mann= 3 , 0 , 0
    10.1      .1       0   103.7    .045       0   118.7     .06       0
Bank Sta=103.7,118.7
XS Rating Curve= 0 ,0
Exp/Cntr=0.3,0.1

Type RM Length L Ch R = 1 ,14106.2 ,143.7,155.9,168.1
XS GIS Cut Line= 2
     1699115.925      240549.499     1698984.344      240366.318
#Sta/Elev= 25
     9.8 1191.97    19.6 1190.69    29.4 1187.35    39.2 1184.64      49  1182.2
    58.8 1180.16    68.6 1178.68    78.4 1177.81    88.3 1177.16    98.1 1175.24
   107.9 1172.42   110.2 1171.99   117.7  1170.6   125.2 1171.44   127.5 1171.69
   137.3 1174.08   147.1 1176.28   156.9 1177.72   166.7 1178.31   176.5 1178.81
   186.3 1179.26   196.1 1179.73   205.9 1180.22   215.7 1180.65   225.5 1181.09
#Mann= 3 , 0 , 0
     9.8      .1       0   110.2    .045       0   125.2     .06       0
Bank Sta=110.2,125.2
XS Rating Curve= 0 ,0
Exp/Cntr=0.3,0.1

Type RM Length L Ch R = 1 ,13950.4 ,186.1,189,191.9
XS GIS Cut Line= 2
     1699197.195      240518.539     1699179.135      240296.658
#Sta/Elev= 24
    10.1  1174.6    20.2 1173.85    30.4 1173.44    40.5 1172.88    50.6 1172.46
    60.7 1172.25    70.8 1172.21      81 1171.88    91.1 1171.12   101.2 1169.27
   111.3 1166.77   113.9 1166.46   121.4 1165.56   128.9  1166.2   131.5 1166.43
   141.7 1168.57   151.8 1170.63   161.9 1172.26     172 1172.83   182.1 1173.44
   192.3 1174.26   202.4 1175.04   212.5 1175.85   222.6 1176.62
#Mann= 3 , 0 , 0
       0      .1       0   113.9    .045       0   128.9      .1       0
Bank Sta=113.9,128.9
XS Rating Curve= 0 ,0
Exp/Cntr=0.3,0.1

Type RM Length L Ch R = 1 ,13761.4 ,232.8,232.2,231.7
XS GIS Cut Line= 2
     1699359.736      240580.459     1699375.216      240279.888
#Sta/Elev= 25
      10 1188.98    20.1 1185.16    30.1 1178.51    40.1 1172.77    50.2 1169.64
    60.2 1168.72    90.3 1167.54   110.4  1166.9   120.4 1166.67   130.4 1165.38
   140.5 1162.58     143 1162.15   150.5 1160.86     158 1161.16   160.5 1161.26
   170.5 1163.02   180.6 1165.06   190.6 1166.54   200.6 1167.37   210.7 1167.84
   220.7 1168.16   230.7 1168.31   250.8 1169.27   290.9  1171.9     301 1172.65
#Mann= 3 , 0 , 0
       0      .1       0     143    .045       0     158      .1       0
Bank Sta=143,158
XS Rating Curve= 0 ,0
Exp/Cntr=0.3,0.1

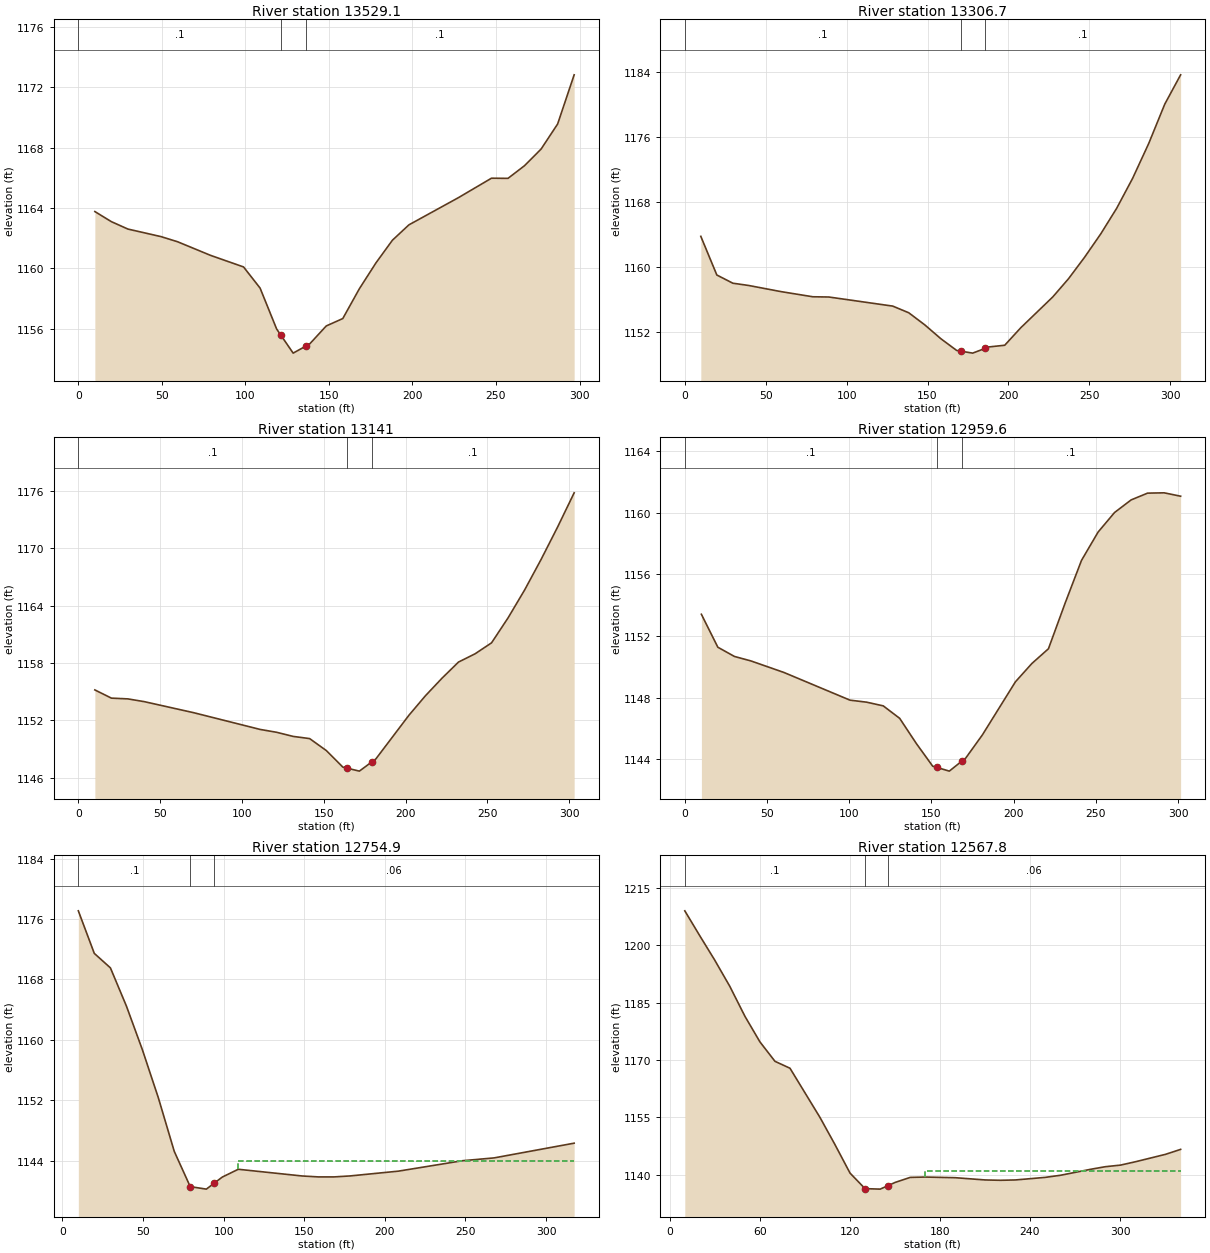
Type RM Length L Ch R = 1 ,13529.1 ,229.9,222.5,215
XS GIS Cut Line= 2
     1699588.779      240529.552     1699596.519      240232.851
#Sta/Elev= 26
     9.9 1163.77    19.8  1163.1    29.7 1162.61    49.5 1162.11    59.4 1161.77
    79.1 1160.87    98.9  1160.1   108.8  1158.7   118.7 1155.99   121.1  1155.6
   128.6 1154.39   136.1 1154.85   138.5    1155   148.4 1156.19   158.3 1156.68
   168.2 1158.65   178.1 1160.36     188 1161.87   197.9 1162.89   227.5 1164.69
   247.3 1165.98   257.2 1165.97   267.1 1166.81     277 1167.91   286.9 1169.57
   296.8 1172.83
#Mann= 3 , 0 , 0
       0      .1       0   121.1    .045       0   136.1      .1       0
Bank Sta=121.1,136.1
XS Rating Curve= 0 ,0
Exp/Cntr=0.3,0.1

Type RM Length L Ch R = 1 ,13306.7 ,161.7,165.7,169.7
XS GIS Cut Line= 2
     1699842.198      240481.129     1699751.897      240188.298
#Sta/Elev= 27
     9.9 1163.77    19.8 1159.01    29.7    1158    39.5 1157.72    59.3 1156.97
    79.1 1156.33      89  1156.3   128.5 1155.18   138.4 1154.36   148.3 1152.87
   158.2 1151.17     168 1149.72   170.4 1149.64   177.9 1149.39   185.4 1149.96
   187.8 1150.15   197.7 1150.36   207.6 1152.51   227.4 1156.31   237.2 1158.57
   247.1 1161.21     257 1164.06   266.9 1167.23   276.8 1170.94   286.7 1175.21
   296.6 1180.05   306.4 1183.66
#Mann= 3 , 0 , 0
       0      .1       0   170.4    .045       0   185.4      .1       0
Bank Sta=170.4,185.4
XS Rating Curve= 0 ,0
Exp/Cntr=0.3,0.1

Type RM Length L Ch R = 1 ,13141   ,172.7,181.4,190.1
XS GIS Cut Line= 2
      1699972.77      240447.263     1699935.682      240146.437
#Sta/Elev= 26
    10.1 1155.19    20.2 1154.33    30.3 1154.25    40.4 1153.96    70.7  1152.8
   111.1 1151.06   121.2 1150.76   131.3 1150.33   141.4  1150.1   151.6 1148.85
   161.7 1147.12   164.3 1147.01   171.8  1146.7   179.3 1147.65   181.9 1147.98
   202.1 1152.54   212.2 1154.58   222.3 1156.41   232.4  1158.1   242.5 1158.96
   252.6 1160.11   262.7 1162.72   272.8 1165.63   282.9 1168.83     293 1172.22
   303.1 1175.79
#Mann= 3 , 0 , 0
       0      .1       0   164.3    .045       0   179.3      .1       0
Bank Sta=164.3,179.3
XS Rating Curve= 0 ,0
Exp/Cntr=0.3,0.1

Type RM Length L Ch R = 1 ,12959.6 ,196.9,204.7,212.5
XS GIS Cut Line= 2
     1700088.589      240432.109     1700165.989      240140.568
#Sta/Elev= 27
    10.1 1153.41    20.1 1151.27    30.2 1150.67    40.2 1150.38    60.3 1149.63
   100.5 1147.83   110.6  1147.7   120.7 1147.46   130.7 1146.65   140.8 1145.02
   150.8 1143.54   153.4 1143.46   160.9 1143.22   168.4 1143.86   170.9 1144.07
     181 1145.57   201.1 1149.02   211.1 1150.21   221.2 1151.17   231.3 1154.12
   241.3 1156.91   251.4 1158.75   261.4 1160.02   271.5 1160.84   281.5 1161.28
   291.6  1161.3   301.6 1161.08
#Mann= 3 , 0 , 0
       0      .1       0   153.4    .045       0   168.4      .1       0
Bank Sta=153.4,168.4
XS Rating Curve= 0 ,0
Exp/Cntr=0.3,0.1

Type RM Length L Ch R = 1 ,12754.9 ,190.3,187.1,183.8
XS GIS Cut Line= 2
      1700244.68      240460.489     1700423.991      240198.618
#Sta/Elev= 20
     9.9 1177.09    19.8 1171.45    29.8 1169.53    39.7 1164.48    49.6  1158.7
    59.5 1152.33    69.4 1145.21    79.3 1140.54    89.3 1140.21    94.31141.017
    99.2 1141.81   109.1 1142.84   148.8 1141.95   158.7 1141.83   168.6 1141.83
   178.5 1141.96   208.3 1142.59     248 1143.97   267.8 1144.35   317.4  1146.3
#Mann= 3 , 0 , 0
     9.9      .1       0    79.3    .045       0    94.3     .06       0
#XS Ineff= 2 , 0
       0                   109.1       0    1144
Permanent Ineff=
       F       F
Bank Sta=79.3,94.3
XS Rating Curve= 0 ,0
Exp/Cntr=0.3,0.1

Type RM Length L Ch R = 1 ,12567.8 ,94.8,94.2,93.5
XS GIS Cut Line= 2
      1700380.13        240626.9     1700529.771      240321.168
#Sta/Elev= 29
      10 1209.02      20 1202.49      30 1196.09      40 1189.26    50.1  1181.4
    60.1 1174.71    70.1 1169.64    80.1 1167.83   100.1 1154.95   110.1 1147.83
   120.1  1140.4   130.1 1136.33   140.2  1136.2   145.11137.062   150.2 1137.96
   160.2 1139.27   170.2 1139.36   190.2 1139.19   210.2  1138.6   220.3 1138.51
   230.3  1138.6   250.3 1139.28   260.3 1139.82   280.3 1141.38   290.3 1142.07
   300.3 1142.48   310.4 1143.37   330.4 1145.31   340.4  1146.6
#Mann= 3 , 0 , 0
      10      .1       0   130.1    .045       0   145.1     .06       0
#XS Ineff= 2 , 0
       0                   170.2       0    1141
Permanent Ineff=
       F       F
Bank Sta=130.1,145.1
XS Rating Curve= 0 ,0
Exp/Cntr=0.3,0.1