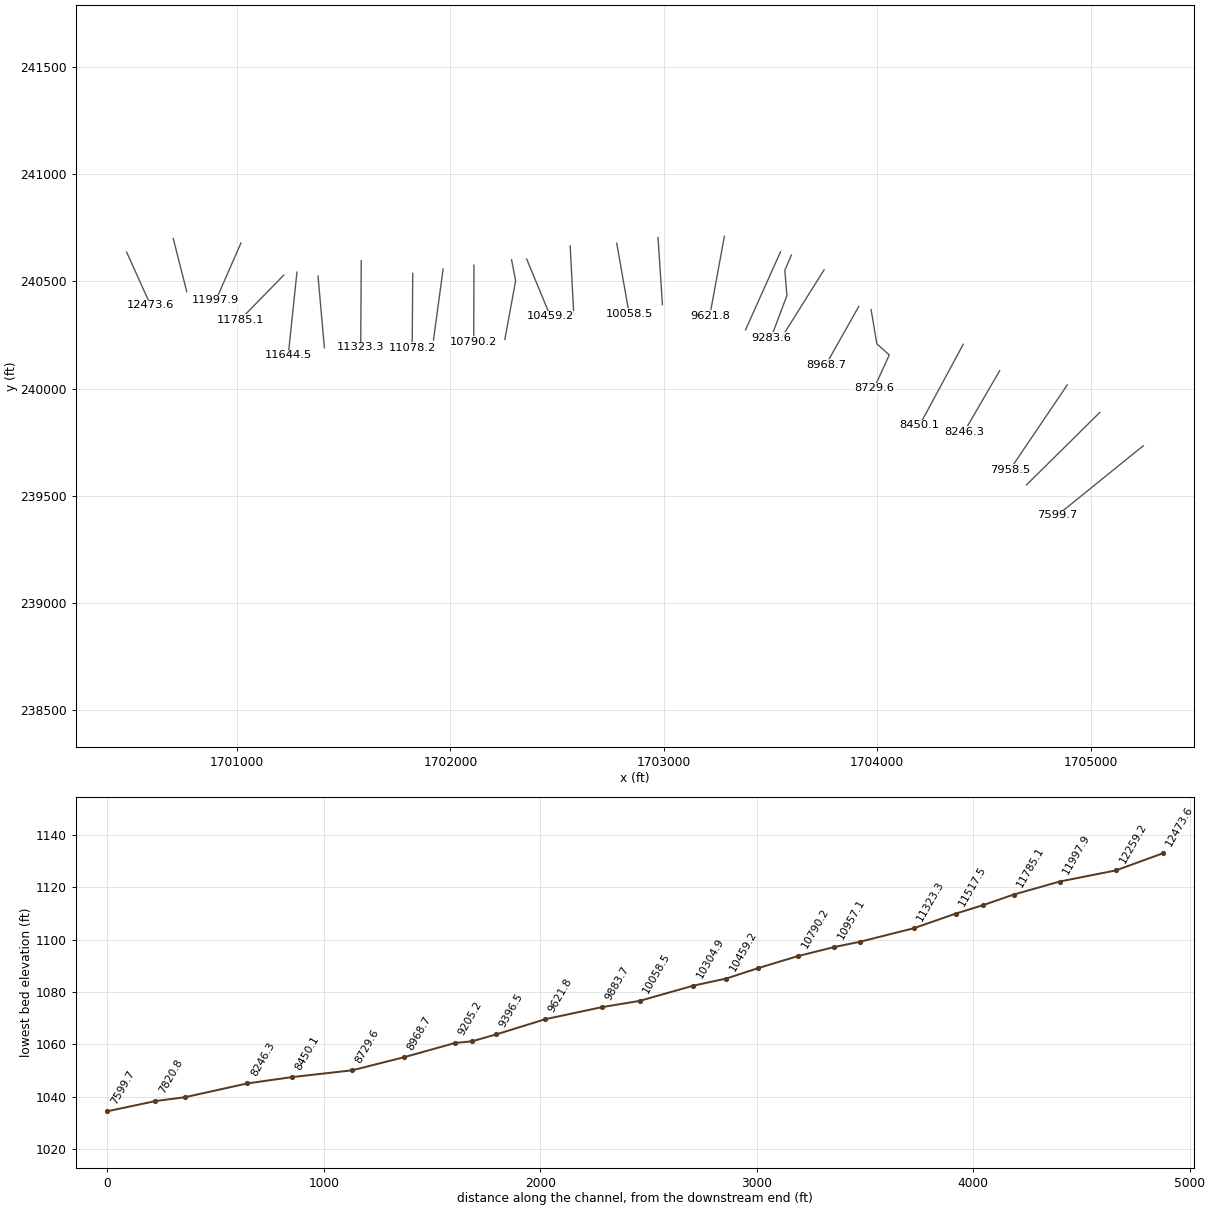
HEC-RAS study brwnngfrk.prj: brwnngfrk

--- brwnngfrk.g01 (geometry) --- (continued)

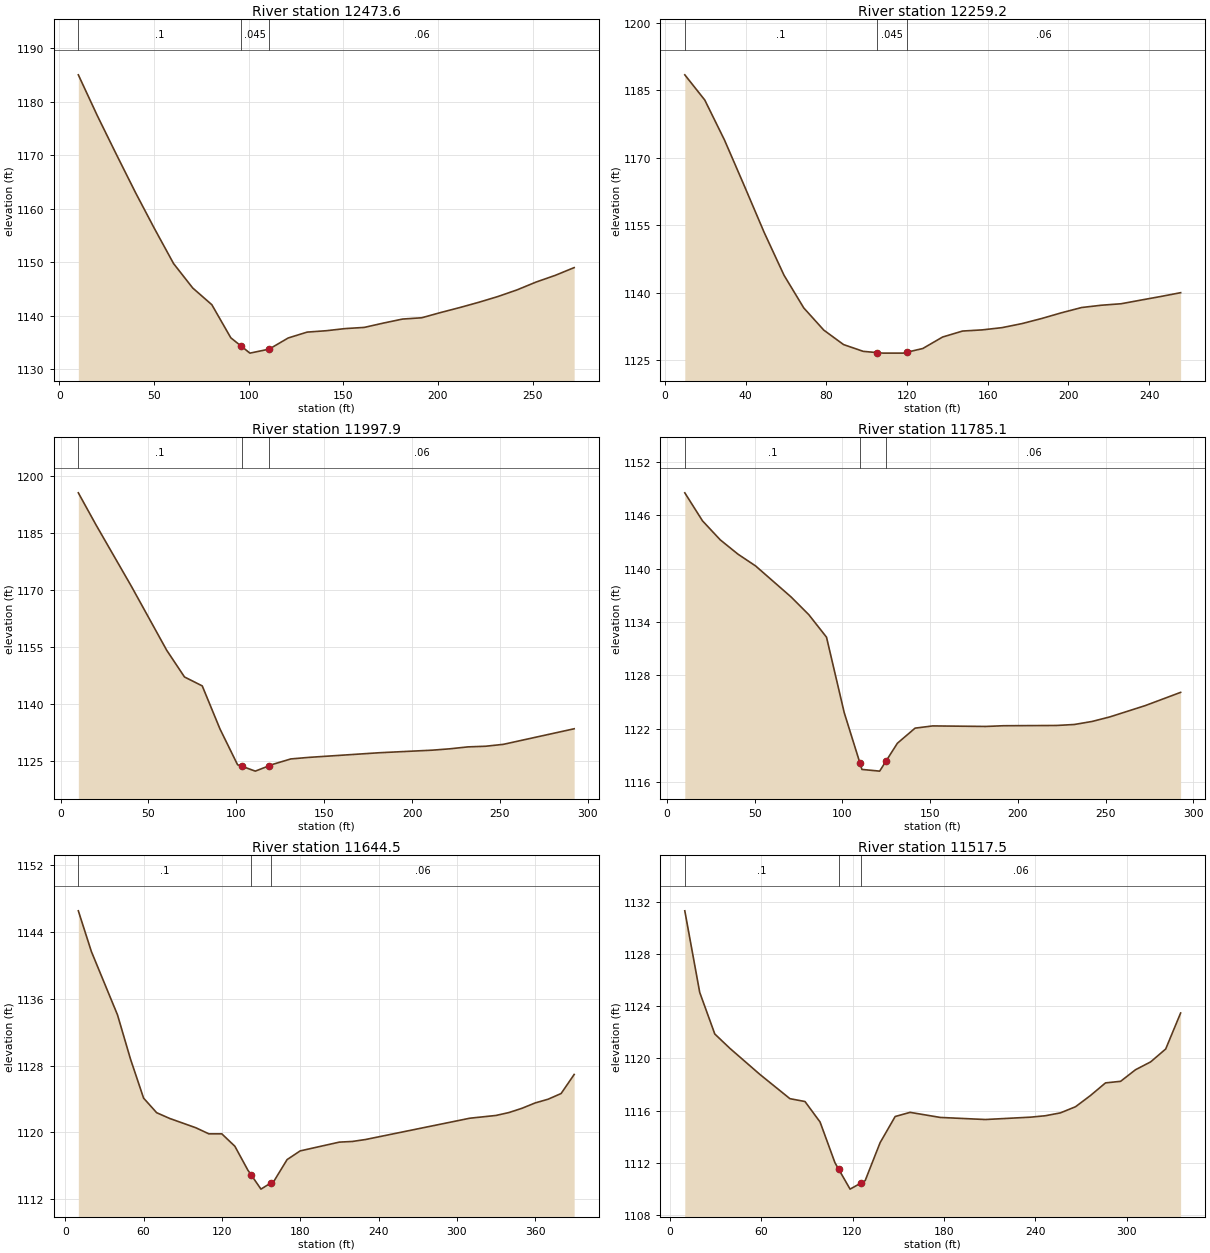
Type RM Length L Ch R = 1 ,12473.6 ,218.6,214.4,210.3
XS GIS Cut Line= 2
     1700482.923        240637.1     1700595.153      240389.418
#Sta/Elev= 30
    10.1 1185.03    20.1 1177.41    30.2 1170.14    40.3    1163    50.4 1156.21
    60.4 1149.73    70.5 1145.17    80.6 1142.04    90.6 1135.86    93.2 1135.12
    95.81134.382   100.7 1132.99   108.2 1133.54   110.8 1133.73   120.9 1135.82
   130.9 1136.92     141 1137.18   151.1 1137.58   161.1  1137.8   171.2 1138.61
   181.3 1139.36   191.4  1139.6   201.4 1140.58   211.5 1141.51   221.6  1142.5
   231.6 1143.57   241.7 1144.81   251.8 1146.28   261.9 1147.53   271.9 1148.98
#Mann= 3 , 0 , 0
    10.1      .1       0    95.8    .045       0   110.8     .06       0
Bank Sta=95.8,110.8
XS Rating Curve= 0 ,0
Exp/Cntr=0.3,0.1

Type RM Length L Ch R = 1 ,12259.2 ,276.2,261.3,246.7
XS GIS Cut Line= 2
     1700701.342       240700.43     1700764.552      240452.749
#Sta/Elev= 30
     9.8 1188.41    19.7 1182.81    29.5 1173.89    39.3 1163.73    49.2 1153.31
      59 1143.83    68.8 1136.56    78.7 1131.64    88.5 1128.42    98.3 1126.91
   100.6 1126.82     1051126.644   108.1 1126.52   115.6 1126.52     118 1126.52
     120 1126.73   127.8 1127.55   137.6  1130.1   147.5 1131.43   157.3 1131.69
   167.1 1132.19     177 1133.09   186.8 1134.23   196.6  1135.5   206.5 1136.66
   216.3 1137.17   226.1  1137.5     236 1138.32   245.8 1139.12   255.6 1139.96
#Mann= 3 , 0 , 0
     9.8      .1       0     105    .045       0     120     .06       0
Bank Sta=105,120
XS Rating Curve= 0 ,0
Exp/Cntr=0.3,0.1

Type RM Length L Ch R = 1 ,11997.9 ,221,212.7,204.6
XS GIS Cut Line= 2
     1701018.614      240679.565     1700900.978      240412.144
#Sta/Elev= 21
    10.1  1195.5    20.1 1187.11    40.3 1170.88    60.4 1154.04    70.5 1147.02
    80.6 1144.67    90.7 1133.32   100.7 1123.91   103.3 1123.48   110.8 1122.23
   118.3 1123.58   120.9 1124.04     131 1125.44     141 1125.84   181.3 1127.07
   211.6 1127.75   221.6 1128.11   231.7 1128.61   241.8 1128.78   251.9 1129.28
   292.2 1133.38
#Mann= 3 , 0 , 0
    10.1      .1       0   103.3    .045       0   118.3     .06       0
Bank Sta=103.3,118.3
XS Rating Curve= 0 ,0
Exp/Cntr=0.3,0.1

Type RM Length L Ch R = 1 ,11785.1 ,125.4,140.6,155.8
XS GIS Cut Line= 2
     1701219.343      240529.675     1701014.232      240320.694
#Sta/Elev= 24
    10.1 1148.51    20.2 1145.36    30.3 1143.23    40.4 1141.62    50.5 1140.29
    70.7 1136.81    80.8 1134.82    90.9 1132.29     101 1123.81     1101118.125
   111.1 1117.43   121.2 1117.24     125 1118.42   131.3 1120.37   141.4 1122.07
   151.5 1122.32   181.8 1122.26   191.8 1122.34   222.1 1122.37   232.2 1122.48
   242.3 1122.82   252.4 1123.33   272.6  1124.6   292.8 1126.09
#Mann= 3 , 0 , 0
    10.1      .1       0     110    .045       0     125     .06       0
Bank Sta=110,125
XS Rating Curve= 0 ,0
Exp/Cntr=0.3,0.1

Type RM Length L Ch R = 1 ,11644.5 ,122.7,127,131.4
XS GIS Cut Line= 2
      1701281.09      240543.766     1701240.236      240156.079
#Sta/Elev= 29
      10  1146.5      20 1141.63      40 1134.06      50 1128.75      60  1124.1
      70 1122.36      80 1121.67     100 1120.56     110 1119.83   119.9 1119.83
   129.9 1118.35   139.9 1115.48   142.4 1114.92   149.9 1113.22   157.4 1113.95
   159.9 1114.19   169.9 1116.75   179.9 1117.79   209.9 1118.84   219.9 1118.92
   229.9 1119.15   309.9  1121.7   329.9 1122.03   339.9 1122.38   349.9 1122.89
   359.8 1123.52   369.8 1123.97   379.8 1124.65   389.8 1126.93
#Mann= 3 , 0 , 0
      10      .1       0   142.4    .045       0   157.4     .06       0
Bank Sta=142.4,157.4
XS Rating Curve= 0 ,0
Exp/Cntr=0.3,0.1

Type RM Length L Ch R = 1 ,11517.5 ,196.3,194.2,192
XS GIS Cut Line= 2
     1701379.885      240524.989     1701409.555      240190.878
#Sta/Elev= 29
     9.9 1131.32    19.7 1125.06    29.6 1121.87    39.5 1120.77    59.2 1118.77
    78.9 1116.91    88.8 1116.69    98.7 1115.12   108.5 1111.99   110.9  1111.5
   118.4 1109.97   125.9 1110.46   128.3 1110.62   138.1 1113.53     148 1115.54
   157.8 1115.86   177.6 1115.47   207.2 1115.31   236.8 1115.49   246.6  1115.6
   256.5 1115.82   266.4 1116.29   276.2 1117.15   286.1 1118.12     296 1118.24
   305.8 1119.13   315.7 1119.73   325.6 1120.72   335.4 1123.48
#Mann= 3 , 0 , 0
     9.9      .1       0   110.9    .045       0   125.9     .06       0
Bank Sta=110.9,125.9
XS Rating Curve= 0 ,0
Exp/Cntr=0.3,0.1

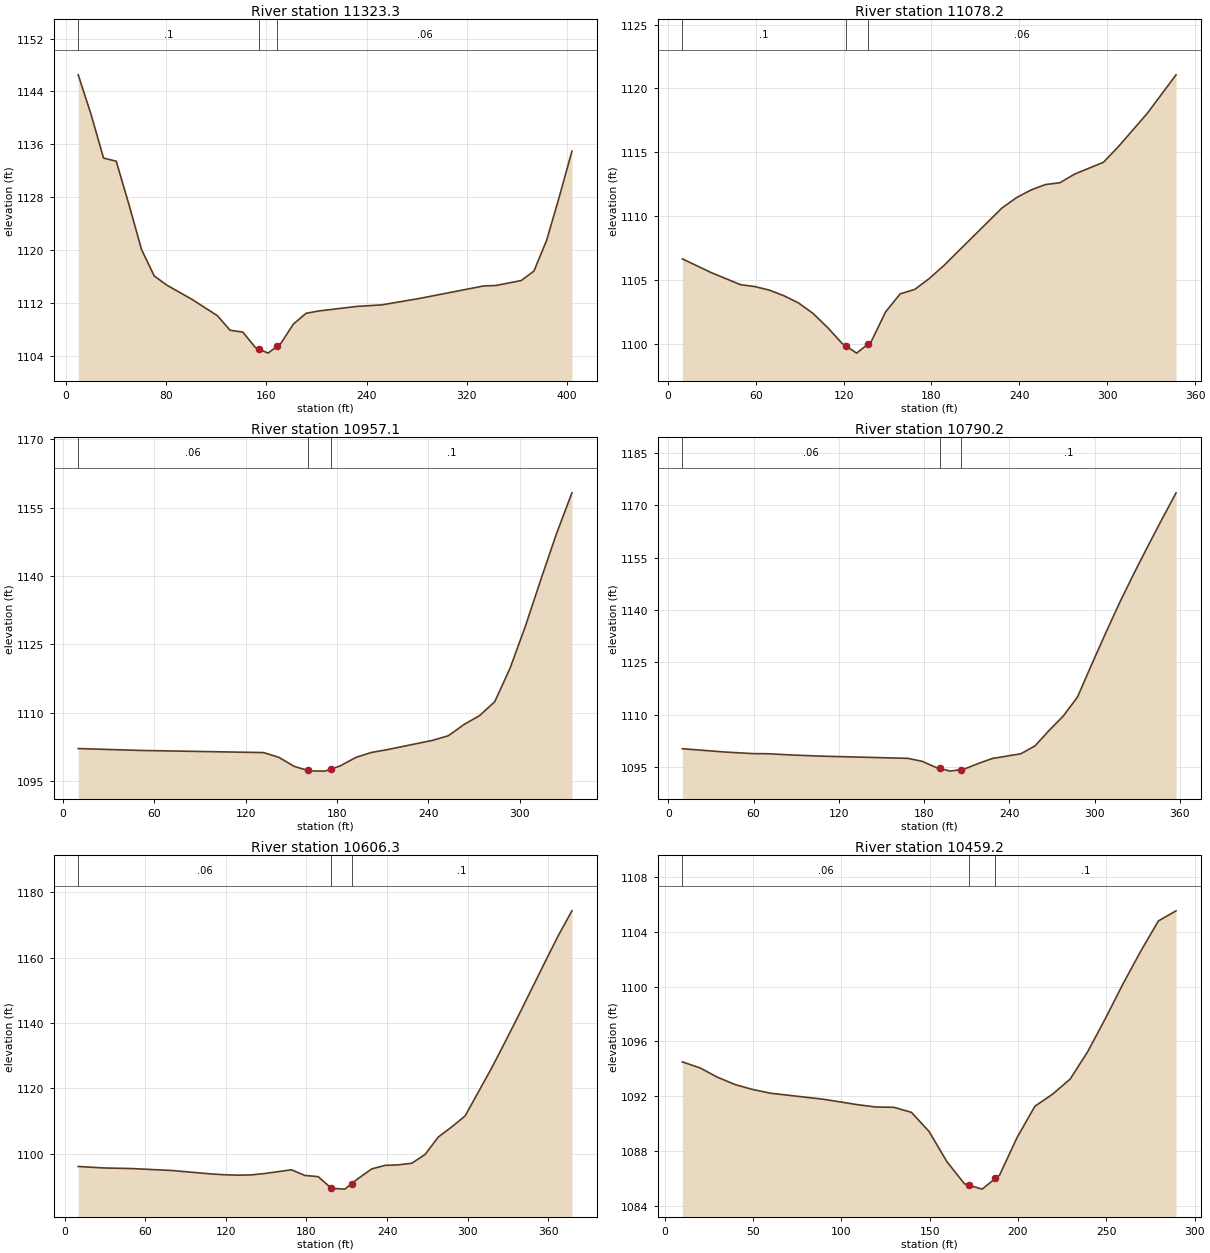
Type RM Length L Ch R = 1 ,11323.3 ,245.1,245.1,245.1
XS GIS Cut Line= 2
     1701582.416      240597.229     1701579.836      240193.458
#Sta/Elev= 30
    10.1 1146.51    20.2  1140.6    30.3 1133.91    40.4 1133.43    50.5 1126.91
    60.6 1120.06    70.7 1116.06    80.8 1114.67   100.9 1112.51   121.1 1110.05
   131.2 1107.84   141.3 1107.57   151.4 1105.23     154 1105.01   161.5 1104.38
     169 1105.46   171.6 1105.83   181.7 1108.78   191.8 1110.41   201.9 1110.76
   232.2 1111.45   252.4 1111.69   282.6 1112.67   333.1 1114.54   343.2 1114.62
   363.4 1115.37   373.5  1116.8   383.6 1121.44   393.7 1128.03   403.8 1134.95
#Mann= 3 , 0 , 0
    10.1      .1       0     154    .045       0     169     .06       0
Bank Sta=154,169
XS Rating Curve= 0 ,0
Exp/Cntr=0.3,0.1

Type RM Length L Ch R = 1 ,11078.2 ,123.9,121,118.2
XS GIS Cut Line= 2
     1701823.647      240537.889     1701821.067      240190.878
#Sta/Elev= 29
     9.9 1106.66    29.7 1105.58    49.6 1104.64    59.5 1104.49    69.4 1104.21
    79.3 1103.77    89.2 1103.21    99.1 1102.39   109.1 1101.28     119 1100.04
   121.4 1099.86   128.9 1099.28   136.4 1099.96   138.8 1100.17   148.7 1102.51
   158.6 1103.92   168.6 1104.27   178.5 1105.12   188.4 1106.13     228 1110.63
     238 1111.45   247.9 1112.05   257.8 1112.48   267.7 1112.62   277.6 1113.29
   297.4 1114.22   307.4 1115.42   327.2 1118.03     347 1121.07
#Mann= 3 , 0 , 0
     9.9      .1       0   121.4    .045       0   136.4     .06       0
Bank Sta=121.4,136.4
XS Rating Curve= 0 ,0
Exp/Cntr=0.3,0.1

Type RM Length L Ch R = 1 ,10957.1 ,164,167,170
XS GIS Cut Line= 2
     1701966.061      240558.543      1701920.86      240227.358
#Sta/Elev= 23
    10.1 1102.17    50.6 1101.76   131.7 1101.29   141.8 1100.26   151.9 1098.26
     1611097.368   162.1 1097.26   172.2 1097.22     1761097.661   182.3 1098.39
   192.5 1100.24   202.6 1101.31   212.7 1101.91   243.1 1103.99   253.2 1104.99
   263.4 1107.44   273.5 1109.36   283.6 1112.44   293.7 1119.81   303.9 1129.16
     314 1139.36   324.1 1149.24   334.3 1158.26
#Mann= 3 , 0 , 0
    10.1     .06       0     161    .045       0     176      .1       0
Bank Sta=161,176
XS Rating Curve= 0 ,0
Exp/Cntr=0.3,0.1

Type RM Length L Ch R = 1 ,10790.2 ,188.3,183.8,179.4
XS GIS Cut Line= 2
     1702110.583      240576.141     1702109.293      240218.809
#Sta/Elev= 27
     9.9  1100.2    39.7 1099.26    59.6  1098.8    69.5 1098.77    89.3 1098.36
   109.2 1098.06   168.7 1097.44   178.7 1096.58   188.6 1094.79     191 1094.54
   198.5 1093.78     206 1094.24   208.4 1094.39   218.4 1096.01   228.3 1097.43
   248.1 1098.75   258.1 1101.03     268 1105.45   277.9 1109.56   287.9 1114.98
   297.8 1124.23   307.7  1133.3   317.6 1142.07   327.6 1150.37   337.5 1158.29
   347.4 1165.98   357.3 1173.55
#Mann= 3 , 0 , 0
     9.9     .06       0     191    .045       0     206      .1       0
Bank Sta=191,206
XS Rating Curve= 0 ,0
Exp/Cntr=0.3,0.1

Type RM Length L Ch R = 1 ,10606.3 ,134.1,147.2,160.3
XS GIS Cut Line= 3
     1702286.759        240601.1     1702305.845      240503.809
     1702255.313      240229.817
#Sta/Elev= 30
     9.9 1096.13    29.7 1095.67    49.6  1095.5    79.3 1094.91   109.1 1093.85
     119  1093.6     129 1093.47   138.9 1093.55   148.9 1093.98   168.8 1095.12
   178.7 1093.39   188.7 1093.02   198.6 1089.46   208.6  1089.2   213.6 1090.84
   218.6 1092.48   228.5 1095.37   238.5 1096.47   248.4 1096.63   258.4 1097.11
   268.3 1099.78   278.3 1105.18   288.2 1108.23   298.2  1111.6   318.1 1126.36
     328 1134.23     338 1142.33   357.9 1158.84   367.8 1166.93   377.8 1174.38
#Mann= 3 , 0 , 0
     9.9     .06       0   198.6    .045       0   213.6      .1       0
Bank Sta=198.6,213.6
XS Rating Curve= 0 ,0
Exp/Cntr=0.3,0.1

Type RM Length L Ch R = 1 ,10459.2 ,162,154.3,146.5
XS GIS Cut Line= 2
     1702357.499      240604.871     1702468.668      240337.617
#Sta/Elev= 28
      10  1094.5      20 1094.06    29.9 1093.38    39.9 1092.84    49.9 1092.48
    59.9 1092.21    89.8 1091.77   109.8 1091.36   119.8  1091.2   129.8 1091.18
   139.7 1090.81   149.7 1089.41   159.7 1087.22   169.7 1085.59   172.2 1085.49
   179.7  1085.2   187.2 1085.98   189.6 1086.23   199.6    1089   209.6 1091.26
   219.6 1092.14   229.6 1093.25   239.5 1095.25   249.5 1097.67   259.5 1100.21
   269.5 1102.59   279.5  1104.8   289.5 1105.54
#Mann= 3 , 0 , 0
      10     .06       0   172.2    .045       0   187.2      .1       0
Bank Sta=172.2,187.2
XS Rating Curve= 0 ,0
Exp/Cntr=0.3,0.1

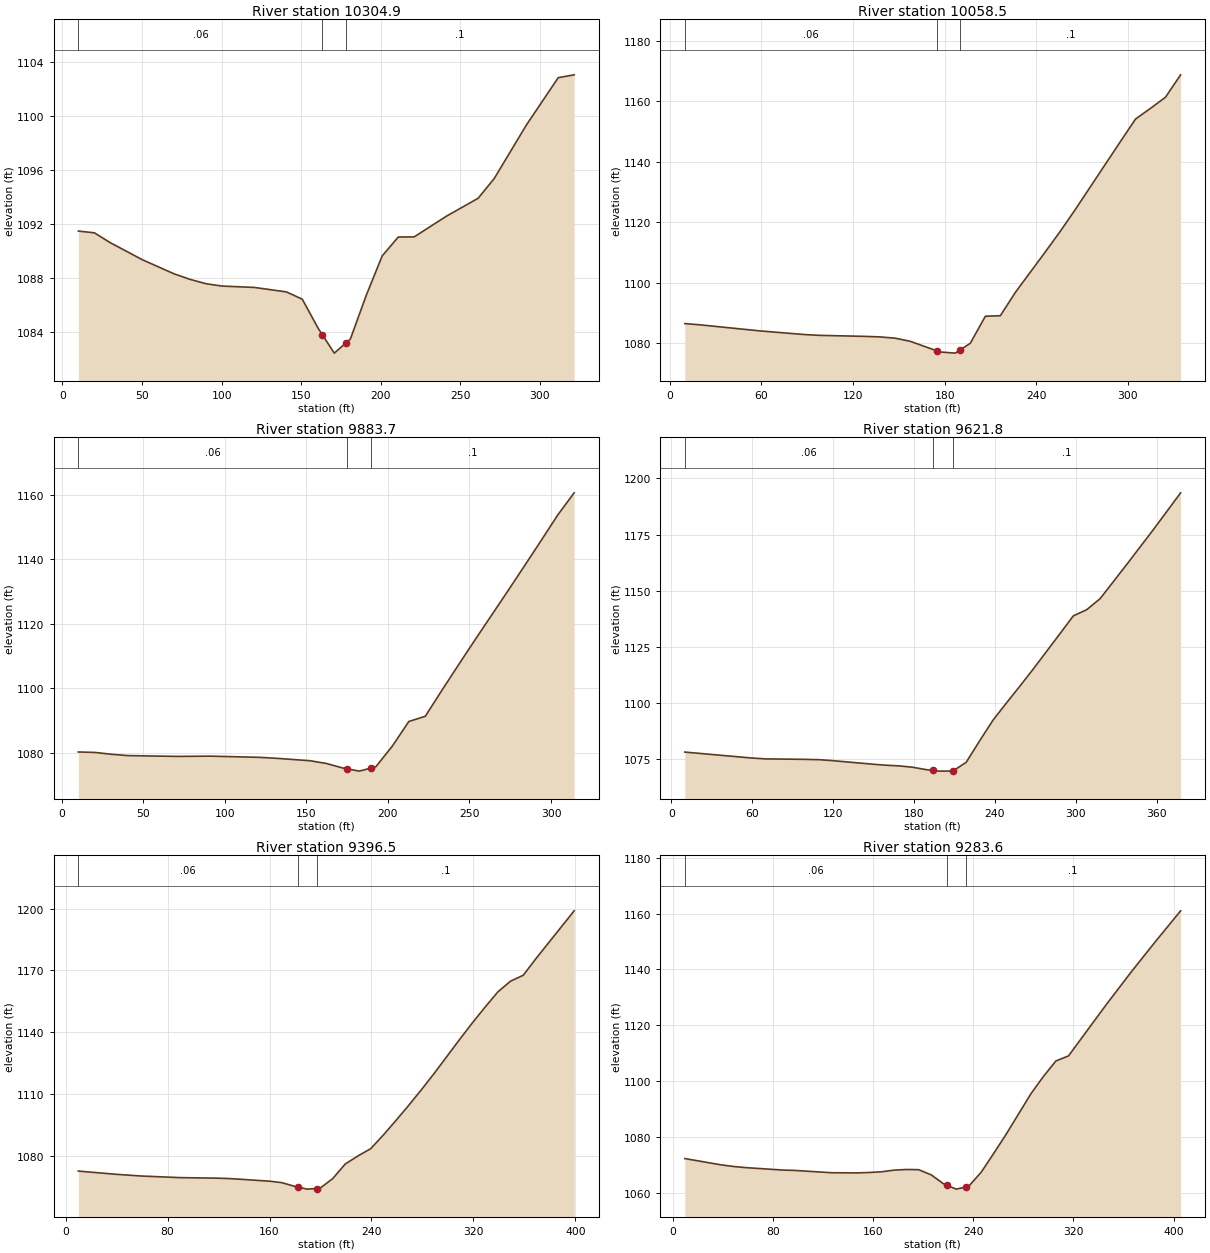
Type RM Length L Ch R = 1 ,10304.9 ,243.6,246.4,249.2
XS GIS Cut Line= 2
     1702561.498      240665.461       1702578.3      240344.388
#Sta/Elev= 26
      10 1091.48    20.1 1091.35    30.1 1090.62    50.2 1089.36    70.3 1088.31
    80.4  1087.9    90.4 1087.58   100.5 1087.41   120.6 1087.31   140.7 1086.98
   150.7 1086.44   160.8 1084.26   163.3 1083.81   170.8 1082.45   178.3 1083.22
   180.9 1083.49   190.9 1086.73   200.9 1089.64     211 1091.04     221 1091.05
   241.1 1092.57   261.2 1093.91   271.3 1095.37   291.4 1099.31   311.5 1102.83
   321.5 1103.04
#Mann= 3 , 0 , 0
      10     .06       0   163.3    .045       0   178.3      .1       0
Bank Sta=163.3,178.3
XS Rating Curve= 0 ,0
Exp/Cntr=0.3,0.1

Type RM Length L Ch R = 1 ,10058.5 ,177.3,174.8,172.4
XS GIS Cut Line= 2
     1702779.541        240678.5      1702837.92      240349.053
#Sta/Elev= 25
     9.8 1086.43    19.7 1086.02      59 1084.01    88.6 1082.79    98.4 1082.53
   127.9  1082.2   137.8 1082.02   147.6  1081.6   157.4 1080.59     1751077.401
   177.1 1077.03     187 1076.66     1901077.656   196.8 1079.91   206.7 1088.86
   216.5 1089.03   226.3 1096.71     246 1110.16   255.9 1117.03   265.7 1124.22
   295.2 1146.65   305.1 1154.09   314.9 1157.61   324.7 1161.29   334.6 1168.69
#Mann= 3 , 0 , 0
     9.8     .06       0     175    .045       0     190      .1       0
Bank Sta=175,190
XS Rating Curve= 0 ,0
Exp/Cntr=0.3,0.1

Type RM Length L Ch R = 1 ,9883.7  ,267.5,261.9,256.3
XS GIS Cut Line= 2
     1702973.042       240705.59     1702993.682      240392.119
#Sta/Elev= 26
    10.1  1080.2    20.3 1080.06    30.4 1079.49    40.5 1079.08    70.9 1078.83
    91.2 1078.91   121.6 1078.53   131.7 1078.23     152  1077.5   162.1 1076.65
   172.3 1075.23   174.9 1074.98   182.4 1074.26   189.9 1075.24   192.5 1075.58
   202.7 1082.03   212.8 1089.66   222.9 1091.28   233.1 1099.34   243.2 1107.18
   253.3 1114.91   273.6 1130.21   283.7 1137.92   293.9 1145.76     304 1153.64
   314.2 1160.61
#Mann= 3 , 0 , 0
    10.1     .06       0   174.9    .045       0   189.9      .1       0
Bank Sta=174.9,189.9
XS Rating Curve= 0 ,0
Exp/Cntr=0.3,0.1

Type RM Length L Ch R = 1 ,9621.8  ,230.8,225.3,219.9
XS GIS Cut Line= 2
     1703283.933       240710.75     1703215.563      240339.228
#Sta/Elev= 28
     9.9 1078.13    59.6 1075.49    69.6  1075.1    99.4 1074.89   109.4 1074.75
   119.3 1074.33   149.1 1072.75   159.1 1072.28     169 1071.98   178.9 1071.39
   188.9 1070.32     1941069.976   198.8 1069.65   208.8 1069.68     2091069.759
   218.7 1073.59   228.6 1083.05   238.6 1092.36   248.5 1099.95   258.5 1107.46
   268.4 1115.08   288.3 1130.86   298.2 1138.79   308.2 1141.56   318.1 1146.47
     338 1161.82   357.9 1177.45   377.8 1193.57
#Mann= 3 , 0 , 0
     9.9     .06       0     194    .045       0     209      .1       0
Bank Sta=194,209
XS Rating Curve= 0 ,0
Exp/Cntr=0.3,0.1

Type RM Length L Ch R = 1 ,9396.5  ,111.4,112.9,114.4
XS GIS Cut Line= 2
     1703547.094       240638.51     1703383.264      240274.728
#Sta/Elev= 30
      10 1072.63    39.9 1071.05    59.8 1070.22    89.8 1069.45   119.7 1069.19
   129.7 1068.96   159.6 1067.75   169.6 1067.02   179.5 1065.26     182 1064.92
   189.5 1063.87     197 1064.17   199.5 1064.27   209.5 1068.92   219.4 1076.06
   229.4 1079.99   239.4 1083.51   249.4 1090.19   259.3 1097.26   269.3  1104.6
   279.3 1112.22   289.3 1120.13   309.2 1136.54   319.2 1144.59   329.2 1152.25
   339.1 1159.57   349.1  1164.8   359.1 1167.67     369 1175.72     399 1198.93
#Mann= 3 , 0 , 0
      10     .06       0     182    .045       0     197      .1       0
Bank Sta=182,197
XS Rating Curve= 0 ,0
Exp/Cntr=0.3,0.1

Type RM Length L Ch R = 1 ,9283.6  ,83,78.4,73.8
XS GIS Cut Line= 4
     1703598.322      240623.961     1703567.408      240552.319
     1703576.986      240434.188     1703502.874        240238.8
#Sta/Elev= 30
     9.8 1072.17      39  1069.9    48.8 1069.32    58.5 1068.92    87.9 1068.05
    97.8 1067.91   127.4 1067.08   147.2 1067.03     157 1067.18   166.9 1067.43
   176.8 1068.02   186.7 1068.25   196.5 1068.18   206.5 1066.31   216.4 1063.09
   218.9 1062.62   226.4 1061.21   233.9 1061.96   236.3  1062.2   246.3 1067.25
   256.3 1073.99   266.2 1080.84   286.1 1095.46   296.1 1101.66     306 1107.18
     316 1108.96   345.8 1127.15   365.7 1138.87   385.6 1150.09   405.5    1161
#Mann= 3 , 0 , 0
     9.8     .06       0   218.9    .045       0   233.9      .1       0
Bank Sta=218.9,233.9
XS Rating Curve= 0 ,0
Exp/Cntr=0.3,0.1

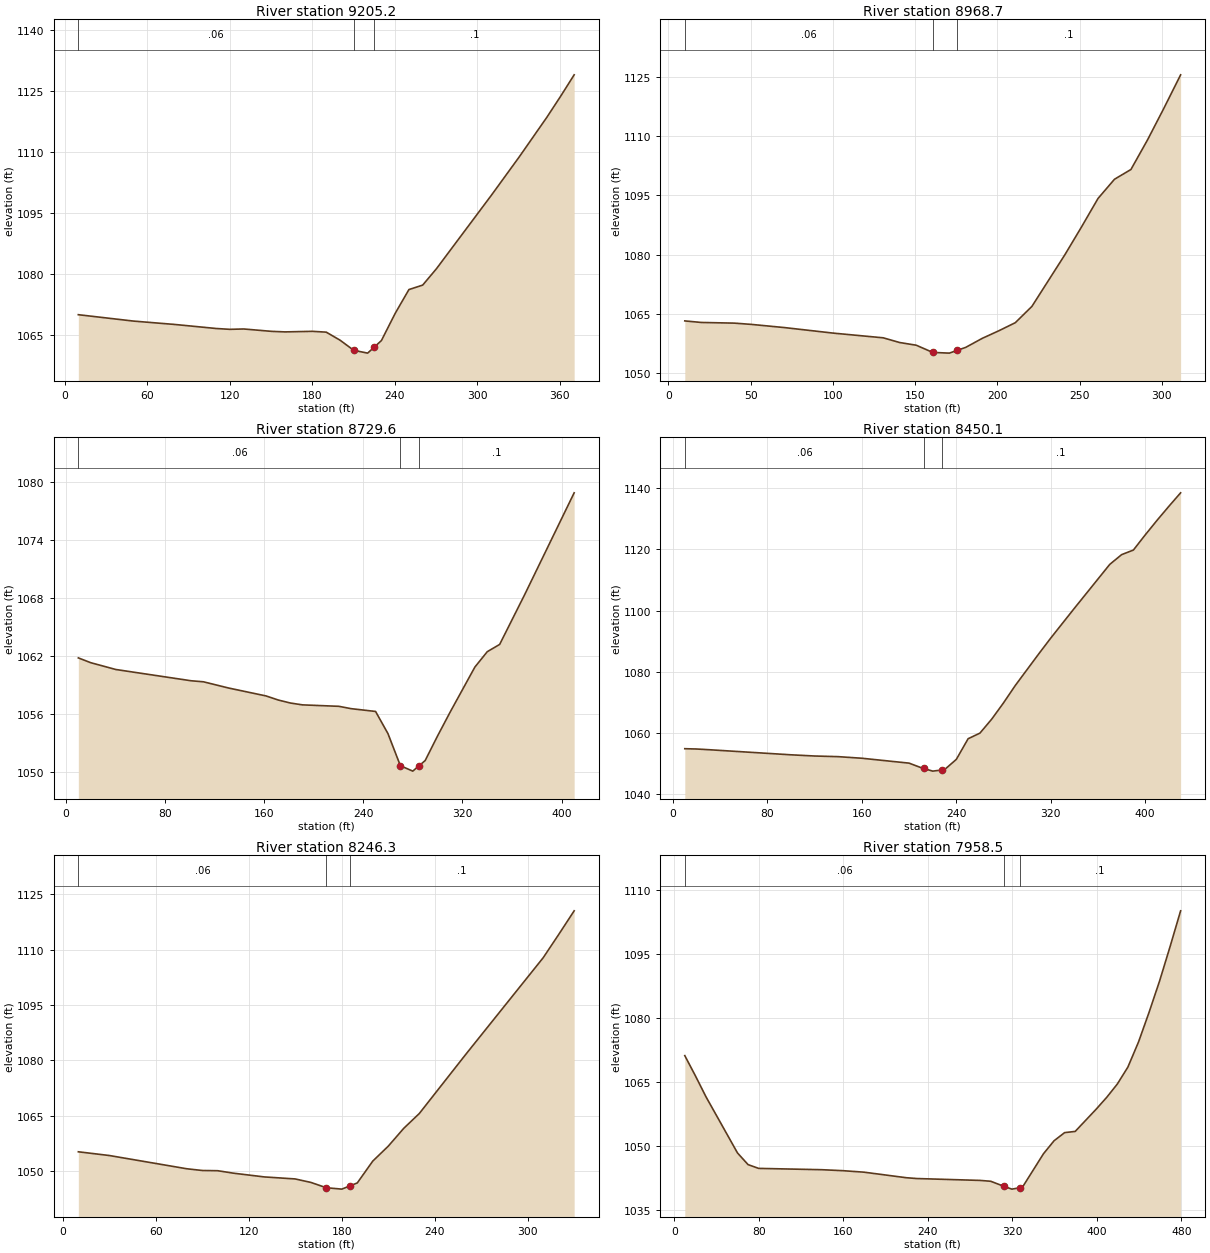
Type RM Length L Ch R = 1 ,9205.2  ,235.5,236.5,237.5
XS GIS Cut Line= 2
     1703751.269      240554.539     1703553.898      240241.068
#Sta/Elev= 24
      10 1070.02    50.1 1068.45    80.1 1067.62   110.1 1066.63   120.1 1066.42
   130.2 1066.51   150.2 1065.93   160.2 1065.79   180.2 1065.93   190.2 1065.73
   200.2 1063.76   210.2 1061.26   220.3 1060.57   225.21062.079   230.3 1063.66
   240.3 1070.34   250.3  1076.2   260.3  1077.3   270.3 1081.32   310.4 1099.47
   330.4 1108.79   350.4 1118.49   360.4 1123.65   370.4 1129.01
#Mann= 3 , 0 , 0
      10     .06       0   210.2    .045       0   225.2      .1       0
Bank Sta=210.2,225.2
XS Rating Curve= 0 ,0
Exp/Cntr=0.3,0.1

Type RM Length L Ch R = 1 ,8968.7  ,237.2,239.1,241.1
XS GIS Cut Line= 2
     1703913.456      240383.089     1703759.945      240112.187
#Sta/Elev= 25
      10 1063.25    20.1 1062.86    40.2 1062.69    50.2 1062.38    70.3 1061.58
   100.4 1060.16   130.6 1058.98   140.6 1057.79   150.7 1057.11   160.7 1055.29
   170.8 1055.11   175.71055.822   180.8 1056.57   190.8 1058.84   200.9 1060.76
   210.9  1062.8     221 1066.92   241.1 1080.01   251.1 1086.96   261.2  1094.2
   271.2 1099.05   281.2 1101.52   291.3 1109.01   301.3 1117.05   311.4 1125.44
#Mann= 3 , 0 , 0
      10     .06       0   160.7    .045       0   175.7      .1       0
Bank Sta=160.7,175.7
XS Rating Curve= 0 ,0
Exp/Cntr=0.3,0.1

Type RM Length L Ch R = 1 ,8729.6  ,281,279.5,277.9
XS GIS Cut Line= 4
     1703971.506      240368.898     1703998.372      240209.538
     1704056.647      240157.338     1703985.696      240002.537
#Sta/Elev= 25
    10.1 1061.81    20.2 1061.31    40.4 1060.61     101 1059.45   111.1 1059.34
   131.3  1058.7   161.6 1057.88   171.4 1057.46   181.2 1057.15   190.9 1056.96
   220.3 1056.81   230.1 1056.57   249.9 1056.28   259.9 1053.99   269.9 1050.68
   279.9 1050.12   284.91050.667   289.9 1051.21   299.9 1053.75     310  1056.2
     330 1060.86     340 1062.45     350  1063.2   370.1 1068.32   410.1 1078.85
#Mann= 3 , 0 , 0
    10.1     .06       0   269.9    .045       0   284.9      .1       0
Bank Sta=269.9,284.9
XS Rating Curve= 0 ,0
Exp/Cntr=0.3,0.1

Type RM Length L Ch R = 1 ,8450.1  ,204.5,203.8,203.1
XS GIS Cut Line= 2
     1704403.658      240207.648     1704198.547      239829.676
#Sta/Elev= 29
      10 1054.85      20 1054.75      30 1054.53     100 1052.85     120 1052.46
     140 1052.25     160 1051.73     200 1050.13     210 1048.67   212.5 1048.38
     220 1047.52   227.5 1047.88     230    1048     240 1051.36     250 1058.11
     260 1059.94     270 1064.52     280 1069.84     290 1075.54     310 1085.93
     320 1091.01     340 1100.74     370  1115.1     380 1118.27     390 1119.78
     400 1124.72     410 1129.48     420 1134.05     430 1138.48
#Mann= 3 , 0 , 0
      10     .06       0   212.5    .045       0   227.5      .1       0
Bank Sta=212.5,227.5
XS Rating Curve= 0 ,0
Exp/Cntr=0.3,0.1

Type RM Length L Ch R = 1 ,8246.3  ,289.4,287.8,286.3
XS GIS Cut Line= 2
     1704573.939      240083.807     1704407.528      239798.716
#Sta/Elev= 21
      10 1055.25      30 1054.24      80 1050.65      90 1050.18     100 1050.12
     110 1049.46     130 1048.44     150 1047.89   160.1 1046.95   170.1 1045.51
   180.1 1045.13   185.1 1045.97   190.1 1046.81   200.1 1052.73   210.1 1056.78
   220.1 1061.61   230.1 1065.61   260.1 1081.64   310.1 1107.84   320.1 1114.13
   330.1 1120.56
#Mann= 3 , 0 , 0
      10     .06       0   170.1    .045       0   185.1      .1       0
Bank Sta=170.1,185.1
XS Rating Curve= 0 ,0
Exp/Cntr=0.3,0.1

Type RM Length L Ch R = 1 ,7958.5  ,142.2,137.7,133.3
XS GIS Cut Line= 2
     1704890.799      240017.586     1704621.299      239621.196
#Sta/Elev= 30
      10 1071.15      20 1066.44      30 1061.53    59.9 1048.34    69.9 1045.61
    79.9 1044.73   139.8 1044.42   159.8 1044.19   179.7 1043.84   219.7 1042.54
   229.7 1042.35   289.6 1041.91   299.6 1041.71   312.1 1040.52   319.6 1039.87
   327.1 1040.19   329.5 1040.29   349.5 1048.16   359.5  1051.2   369.5 1053.11
   379.5 1053.39   399.4 1058.61   409.4 1061.39   419.4  1064.5   429.4 1068.47
   439.4 1074.32   449.4 1081.27   459.4 1088.65   469.3 1096.68   479.3 1105.08
#Mann= 3 , 0 , 0
      10     .06       0   312.1    .045       0   327.1      .1       0
Bank Sta=312.1,327.1
XS Rating Curve= 0 ,0
Exp/Cntr=0.3,0.1

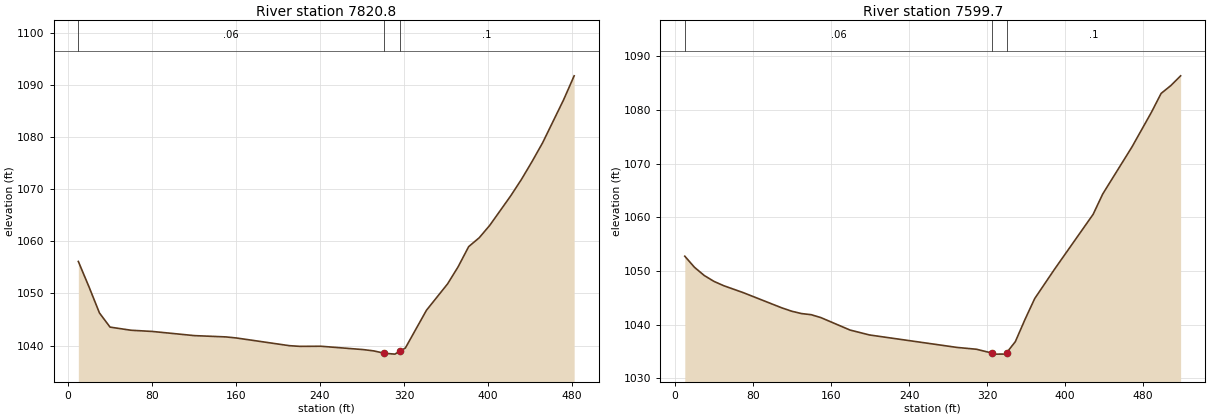
Type RM Length L Ch R = 1 ,7820.8  ,223.3,221.1,218.8
XS GIS Cut Line= 2
     1705043.516      239889.573     1704699.903      239551.575
#Sta/Elev= 30
      10 1056.14    20.1  1051.3    30.1 1046.27    40.2 1043.55    60.2 1042.95
    80.3 1042.72   120.5 1041.92   150.6 1041.67   160.7 1041.46   210.9 1039.99
   220.9 1039.86     241 1039.88   281.2 1039.24   291.2 1038.99   301.2 1038.54
   311.3 1038.37   316.21038.938   321.3 1039.54   341.4 1046.78   361.5 1051.84
   371.5  1055.1   381.6 1058.99   391.6 1060.68   401.7 1063.08   421.7 1068.75
   431.8 1071.87   441.8 1075.26   451.9 1078.87   471.9 1087.12     482 1091.74
#Mann= 3 , 0 , 0
      10     .06       0   301.2    .045       0   316.2      .1       0
Bank Sta=301.2,316.2
XS Rating Curve= 0 ,0
Exp/Cntr=0.3,0.1

Type RM Length L Ch R = 1 ,7599.7  ,229.4,237,244.7
XS GIS Cut Line= 2
     1705247.322      239734.216      1704843.55      239409.134
#Sta/Elev= 30
      10 1052.75    19.9 1050.69    29.9 1049.16    39.9 1048.06    49.8 1047.26
    69.8 1045.97   109.7 1043.11   119.6  1042.5   129.6 1042.06   139.6 1041.85
   149.5 1041.31   179.4 1038.99   199.4 1038.07   289.1 1035.75     309 1035.41
     3251034.697     329  1034.5   338.9 1034.51     3401034.764   348.9 1036.82
   358.9 1040.99   368.8 1044.86   388.8 1050.24   428.7 1060.56   438.6 1064.37
   468.5 1073.11   488.5 1079.59   498.4 1083.09   508.4 1084.56   518.4 1086.37
#Mann= 3 , 0 , 0
      10     .06       0     325    .045       0     340      .1       0
Bank Sta=325,340
XS Rating Curve= 0 ,0
Exp/Cntr=0.3,0.1