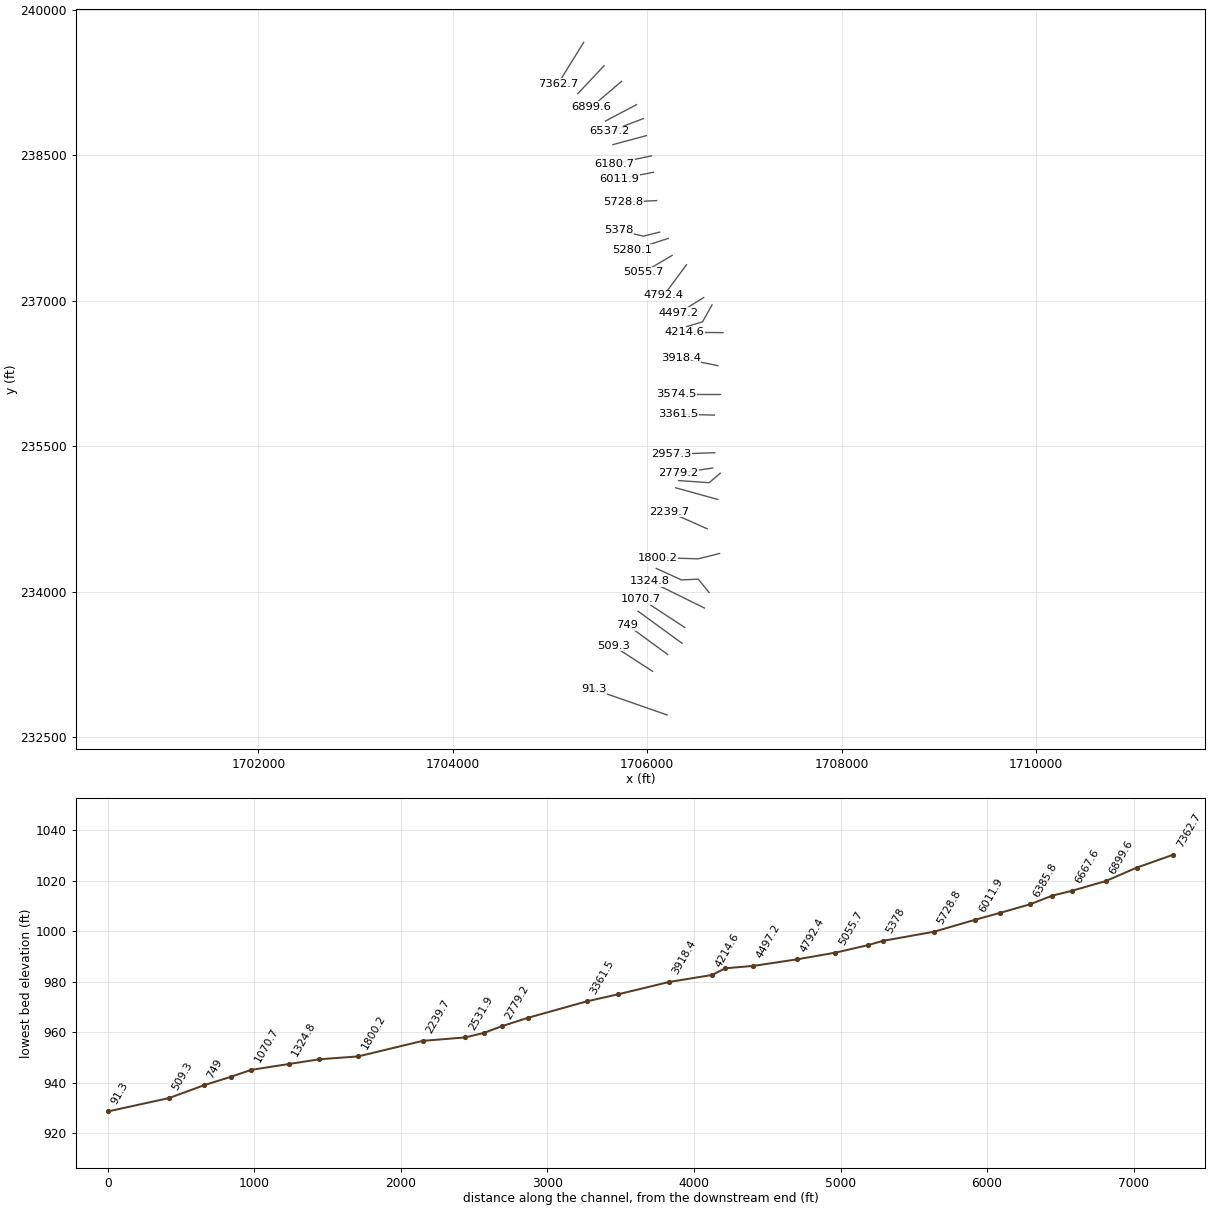
HEC-RAS study brwnngfrk.prj: brwnngfrk

--- brwnngfrk.g01 (geometry) --- (continued)

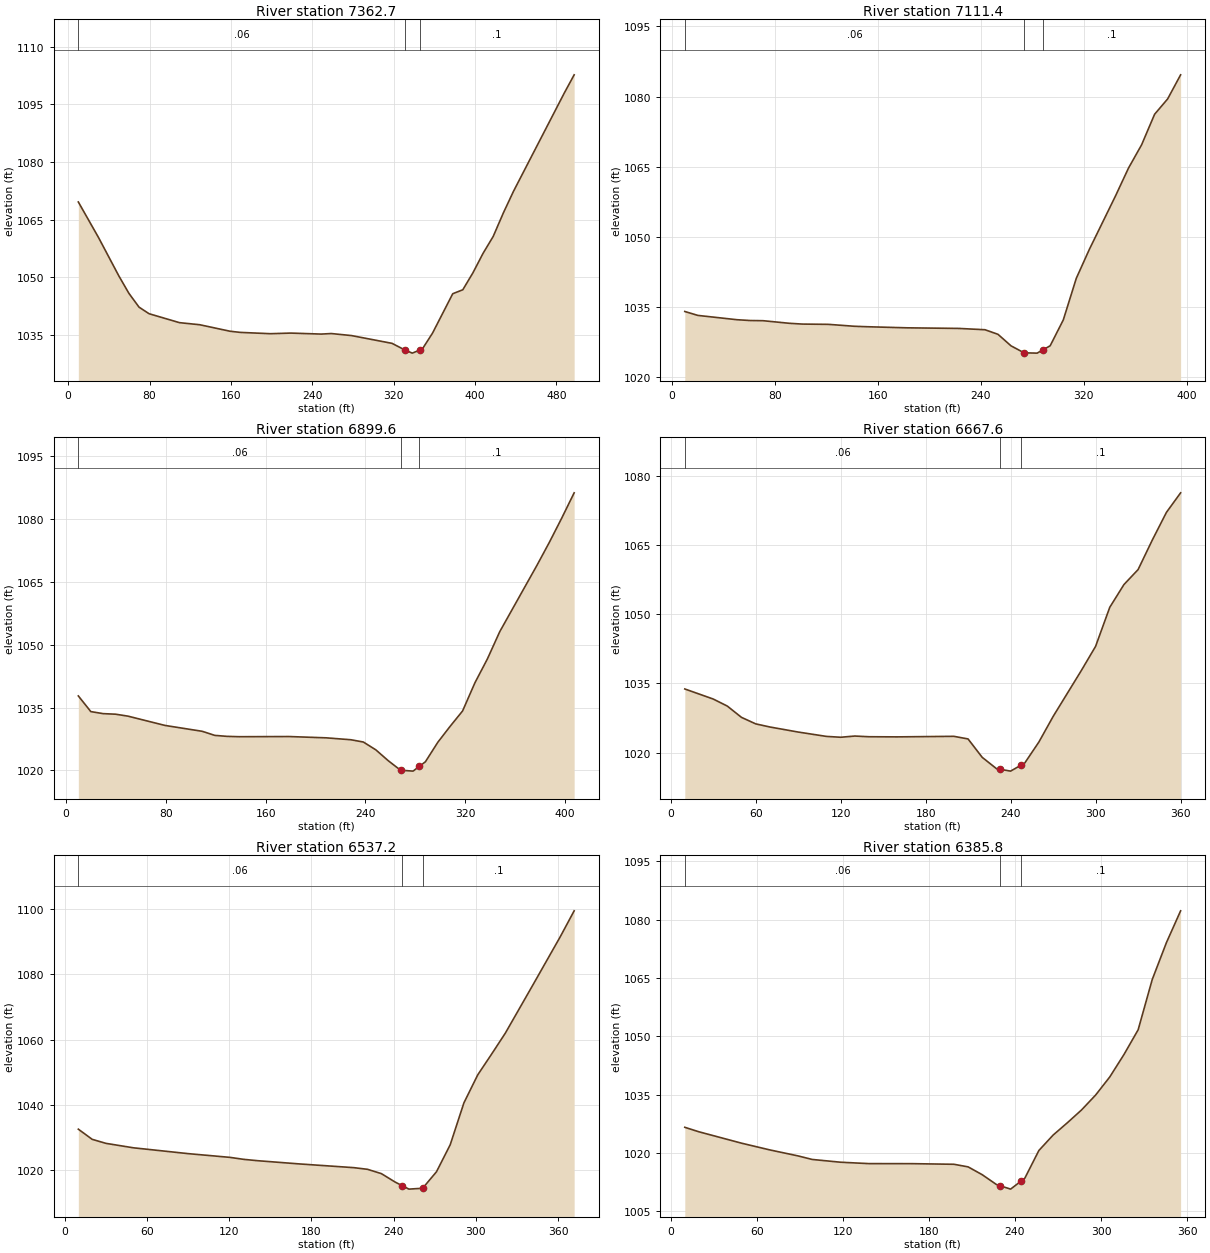
Type RM Length L Ch R = 1 ,7362.7  ,255.8,251.2,246.7
XS GIS Cut Line= 2
     1705345.315      239660.565     1705083.444      239237.443
#Sta/Elev= 30
      10  1069.6    29.9 1060.34    49.8  1050.4    59.7 1045.87    69.7 1042.26
    79.6 1040.55   109.5 1038.23   129.4 1037.69   159.2    1036   169.2  1035.7
     199 1035.36   218.9 1035.52   248.8 1035.26   258.8  1035.4   278.7 1034.87
   318.5 1032.85   330.9 1031.16   338.4 1030.31   345.9 1031.12   348.3 1031.38
   358.3  1035.5   378.2 1045.75   388.1 1046.78   398.1 1051.21     408 1056.24
     418 1060.65   427.9 1066.71   437.9 1072.35   487.7 1097.82   497.6 1102.65
#Mann= 3 , 0 , 0
      10     .06       0   330.9    .045       0   345.9      .1       0
Bank Sta=330.9,345.9
XS Rating Curve= 0 ,0
Exp/Cntr=0.3,0.1

Type RM Length L Ch R = 1 ,7111.4  ,214.3,211.9,209.4
XS GIS Cut Line= 2
     1705555.633      239420.744     1705284.732      239133.073
#Sta/Elev= 28
    10.1 1034.05    20.3 1033.21    50.7 1032.29    60.8 1032.12    70.9 1032.08
    91.2 1031.53   101.3 1031.36   121.6  1031.3   141.8 1030.89     152 1030.79
   182.4 1030.56   222.9 1030.43   243.2 1030.15   253.3 1029.17   263.4 1026.71
   273.6 1025.21   283.7 1025.15   288.61025.914   293.8 1026.72     304 1032.25
   314.1 1041.15   324.2 1047.31   344.5 1058.73   354.6 1064.69   364.8 1069.68
   374.9 1076.21     385 1079.48   395.1 1084.64
#Mann= 3 , 0 , 0
    10.1     .06       0   273.6    .045       0   288.6      .1       0
Bank Sta=273.6,288.6
XS Rating Curve= 0 ,0
Exp/Cntr=0.3,0.1

Type RM Length L Ch R = 1 ,6899.6  ,236.9,231.9,226.9
XS GIS Cut Line= 2
     1705736.234      239260.784     1705426.633      238996.333
#Sta/Elev= 30
     9.9 1037.78    19.9 1034.04    29.8 1033.55    39.7 1033.42    49.7 1032.95
    79.4 1030.73   109.2 1029.33   119.2 1028.36   129.1 1028.12     139 1028.04
   178.8 1028.08   208.6 1027.77   228.4 1027.31   238.3 1026.77   248.3  1024.9
   258.2 1022.32   268.1 1020.04   278.1 1019.82   283.11020.947     288 1022.05
   297.9 1026.69   307.9 1030.55   317.8 1034.19   327.7 1040.93   337.7 1046.63
   347.6 1053.14   377.4 1068.98   387.3 1074.45   397.2 1080.22   407.2 1086.29
#Mann= 3 , 0 , 0
     9.9     .06       0   268.1    .045       0   283.1      .1       0
Bank Sta=268.1,283.1
XS Rating Curve= 0 ,0
Exp/Cntr=0.3,0.1

Type RM Length L Ch R = 1 ,6667.6  ,133.1,130.4,127.6
XS GIS Cut Line= 2
     1705889.072      239020.436     1705571.113      238851.852
#Sta/Elev= 30
      10 1033.81      30 1031.63      40 1030.09      50 1027.64      60 1026.23
      70 1025.55      90 1024.45     110  1023.5     120 1023.32     130 1023.58
     140 1023.43   159.9  1023.4   199.9 1023.52   209.9 1022.95   219.9 1018.95
   229.9 1016.51   232.4 1016.37   239.9 1015.96   247.4 1017.28   249.9 1017.72
   259.9 1022.29   269.9 1027.82   289.9 1037.85   299.9 1043.07   309.9 1051.55
   319.9 1056.49   329.9 1059.75   339.9 1066.15   349.9 1072.18   359.9 1076.42
#Mann= 3 , 0 , 0
      10     .06       0   232.4    .045       0   247.4      .1       0
Bank Sta=232.4,247.4
XS Rating Curve= 0 ,0
Exp/Cntr=0.3,0.1

Type RM Length L Ch R = 1 ,6537.2  ,153.8,151.5,149.2
XS GIS Cut Line= 2
     1705959.405      238876.362     1705612.394      238743.491
#Sta/Elev= 25
      10 1032.52    20.1  1029.4    30.1 1028.17    50.2  1026.8    90.4    1025
   120.5 1023.87   130.6 1023.26   140.6 1022.85   170.7 1021.87   210.9 1020.71
   220.9  1020.2     231 1018.88     241  1016.3   246.1  1015.2   251.1 1014.12
   261.1 1014.39   271.2 1019.45   281.2 1027.73   291.2 1040.59   301.3  1049.2
   311.3 1055.49   321.4 1061.99   341.5 1076.77   361.5  1091.6   371.6 1099.53
#Mann= 3 , 0 , 0
      10     .06       0   246.1    .045       0   261.1      .1       0
Bank Sta=246.1,261.1
XS Rating Curve= 0 ,0
Exp/Cntr=0.3,0.1

Type RM Length L Ch R = 1 ,6385.8  ,206.4,205.1,203.7
XS GIS Cut Line= 2
     1705990.365      238700.921     1705647.224      238608.041
#Sta/Elev= 28
     9.9 1026.58    19.7 1025.43    49.4  1022.5    69.1 1020.77    88.9 1019.22
    98.7 1018.31   118.5  1017.6   138.2 1017.24   167.9 1017.23   197.5 1017.07
   207.4  1016.4   217.2 1014.39   227.1 1011.87   229.5 1011.58     237 1010.68
   244.5 1012.81   246.9 1013.49   256.7 1020.61   266.6 1024.57   276.5 1027.73
   286.4 1031.03   296.2 1034.85   306.1 1039.52     316 1045.29   325.9 1051.66
   335.7 1064.57   345.6 1074.07   355.5 1082.25
#Mann= 3 , 0 , 0
     9.9     .06       0   229.5    .045       0   244.5      .1       0
Bank Sta=229.5,244.5
XS Rating Curve= 0 ,0
Exp/Cntr=0.3,0.1

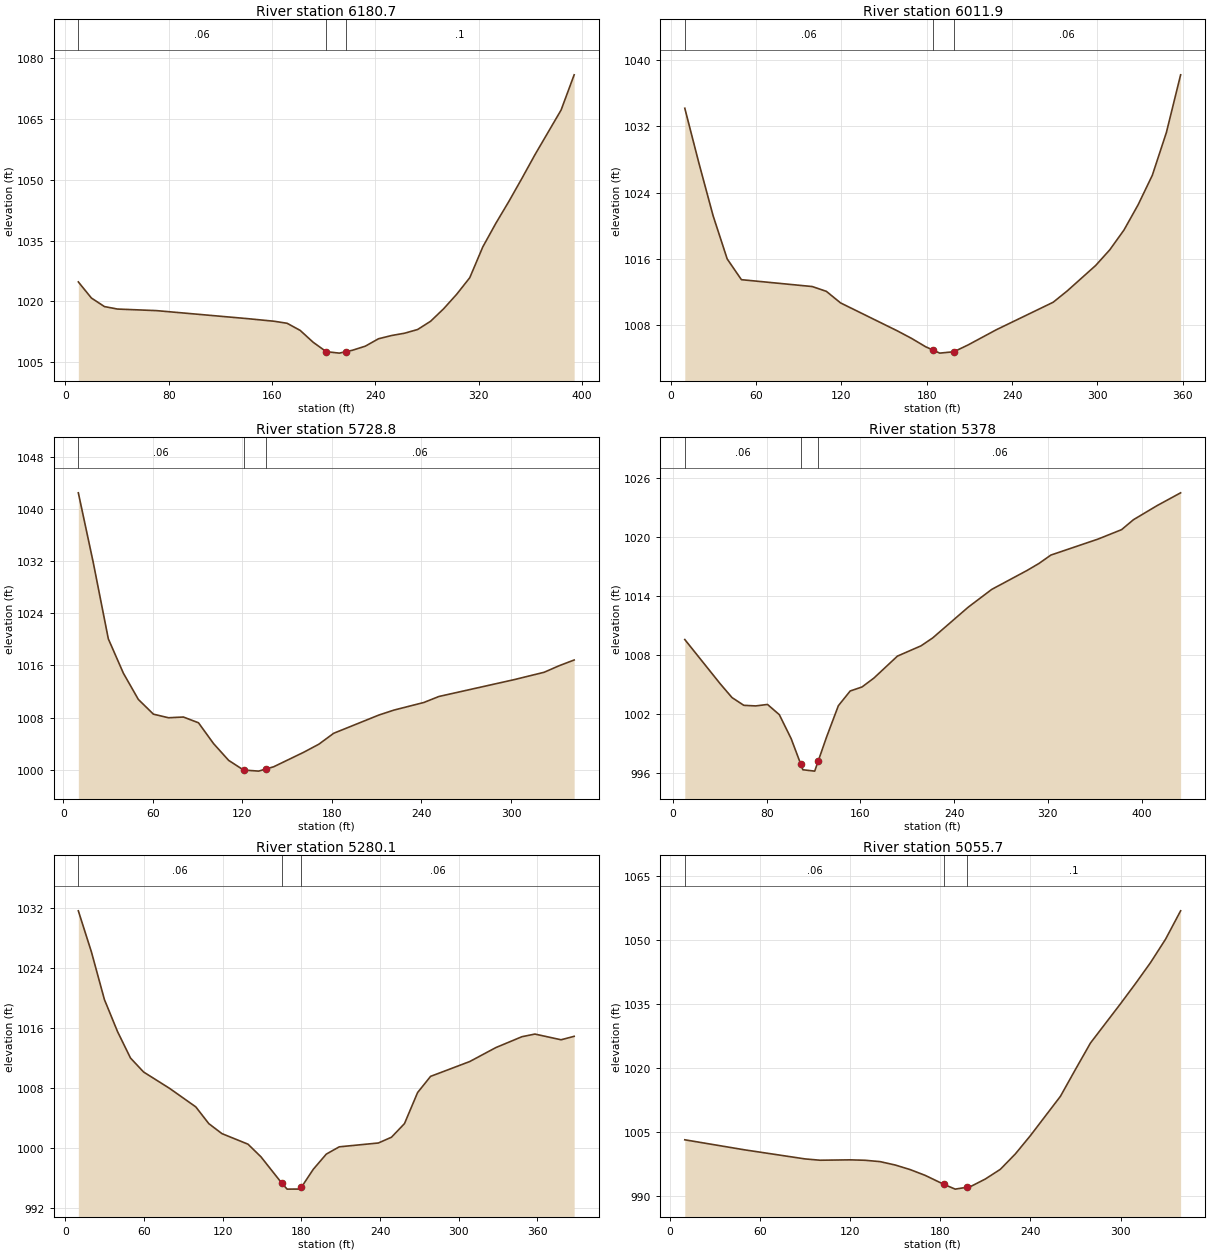
Type RM Length L Ch R = 1 ,6180.7  ,169.1,168.9,168.5
XS GIS Cut Line= 2
     1706043.255       238491.94     1705657.544       238411.96
#Sta/Elev= 30
    10.1 1024.81    20.2 1020.85    30.3 1018.74    40.4 1018.13    70.7 1017.74
   141.4 1015.76   161.6 1015.13   171.7 1014.63   181.8 1012.88   191.9 1009.95
     202 1007.64   212.1 1007.28     217 1007.62   222.2 1007.98   232.3    1009
   242.4 1010.81   252.5 1011.61   262.6 1012.18   272.7 1013.09   282.8 1015.13
   292.9 1018.21     303 1021.78   313.1 1025.85   323.2 1033.44   333.3 1039.25
   343.4 1044.64   353.5 1050.32   363.6 1056.15   383.8 1067.13   393.9 1075.79
#Mann= 3 , 0 , 0
    10.1     .06       0     202    .045       0     217      .1       0
Bank Sta=202,217
XS Rating Curve= 0 ,0
Exp/Cntr=0.3,0.1

Type RM Length L Ch R = 1 ,6011.9  ,286.2,283.1,280
XS GIS Cut Line= 2
     1706063.895      238322.949     1705711.724      238255.869
#Sta/Elev= 25
      10 1034.19    19.9 1027.57    29.9 1021.19    39.8 1015.97    49.8 1013.46
    99.6 1012.63   109.5 1012.05   119.5 1010.65   159.3 1007.28   169.3 1006.37
   179.3 1005.35   184.21004.967   189.2 1004.58   199.2 1004.75   209.1 1005.57
     229 1007.41   268.9 1010.73   278.8  1012.1   298.8 1015.18   308.7 1017.07
   318.7 1019.47   328.6 1022.51   338.6 1026.08   348.5 1031.26   358.5 1038.23
#Mann= 3 , 0 , 0
      10     .06       0   184.2    .045       0   199.2     .06       0
Bank Sta=184.2,199.2
XS Rating Curve= 0 ,0
Exp/Cntr=0.3,0.1

Type RM Length L Ch R = 1 ,5728.8  ,346.6,350.8,355
XS GIS Cut Line= 2
     1706096.146      238031.408     1705754.294      238013.348
#Sta/Elev= 26
    10.1 1042.46    20.1 1031.78    30.2 1020.08    40.3 1014.81    50.3  1010.8
    60.4 1008.54    70.5 1007.99    80.5  1008.1    90.6 1007.22   100.7 1004.03
   110.8 1001.46   120.8  999.98   130.9  999.81   135.81000.137     141 1000.48
   161.1  1002.7   171.2 1003.93   181.2 1005.61   211.4  1008.4   221.5 1009.16
   241.6 1010.33   251.7 1011.25   302.1 1013.83   322.2 1014.96   332.3 1015.97
   342.3 1016.84
#Mann= 3 , 0 , 0
    10.1     .06       0   120.8    .045       0   135.8     .06       0
Bank Sta=120.8,135.8
XS Rating Curve= 0 ,0
Exp/Cntr=0.3,0.1

Type RM Length L Ch R = 1 ,5378    ,96.2,97.9,99.5
XS GIS Cut Line= 3
     1706127.106      237706.327     1705960.695      237665.047
     1705705.274      237723.097
#Sta/Elev= 30
    10.1 1009.56    40.3 1005.06    50.4 1003.65    60.5 1002.86    70.6  1002.8
    80.7 1002.95    90.8 1001.91   100.9  999.47     109 996.902   110.9   996.3
     121  996.16     124 997.188   131.1  999.62   141.2 1002.82   151.3 1004.32
   161.4 1004.73   171.5 1005.63   191.6 1007.87   211.8 1008.92   221.8 1009.73
     252 1012.85   272.2 1014.67   302.4  1016.6   312.5 1017.31   322.6 1018.16
   362.9 1019.79     383 1020.75   393.1 1021.76   413.2 1023.19   433.4  1024.5
#Mann= 3 , 0 , 0
    10.1     .06       0     109    .045       0     124     .06       0
Bank Sta=109,124
XS Rating Curve= 0 ,0
Exp/Cntr=0.3,0.1

Type RM Length L Ch R = 1 ,5280.1  ,219.5,224.5,229.4
XS GIS Cut Line= 2
     1706216.116      237641.826     1705847.175      237521.856
#Sta/Elev= 30
     9.9 1031.62    19.9 1026.13    29.8 1019.79    39.8 1015.52    49.7 1011.99
    59.7 1010.13    79.6 1007.94    99.5 1005.48   109.4 1003.25   119.4 1001.92
   139.3 1000.51   149.2  998.82     165 995.329   169.1  994.52   179.1  994.53
     180 994.768     189  997.15     199  999.19   208.9 1000.16   238.7 1000.67
   248.7 1001.44   258.6 1003.25   268.6 1007.39   278.5 1009.55   308.4 1011.53
   328.3 1013.39   348.2 1014.84   358.1 1015.19     378 1014.43     388 1014.89
#Mann= 3 , 0 , 0
     9.9     .06       0     165    .045       0     180     .06       0
Bank Sta=165,180
XS Rating Curve= 0 ,0
Exp/Cntr=0.3,0.1

Type RM Length L Ch R = 1 ,5055.7  ,254.3,263.3,272.4
XS GIS Cut Line= 2
     1706256.106      237466.386     1705963.275      237293.525
#Sta/Elev= 26
      10 1003.11      50 1000.74      90  998.62     100  998.31     120   998.4
     130   998.3     140  997.98     150  997.19     160  996.11     170  994.75
   182.5  992.63     190  991.52   197.5  991.95     200  992.09     210  993.89
     220  996.17     230  999.79     240 1004.08     260 1013.33     270 1019.64
     280 1025.85     300 1035.08     310 1039.83     320 1044.76     330 1050.26
     340 1056.91
#Mann= 3 , 0 , 0
      10     .06       0   182.5    .045       0   197.5      .1       0
Bank Sta=182.5,197.5
XS Rating Curve= 0 ,0
Exp/Cntr=0.3,0.1

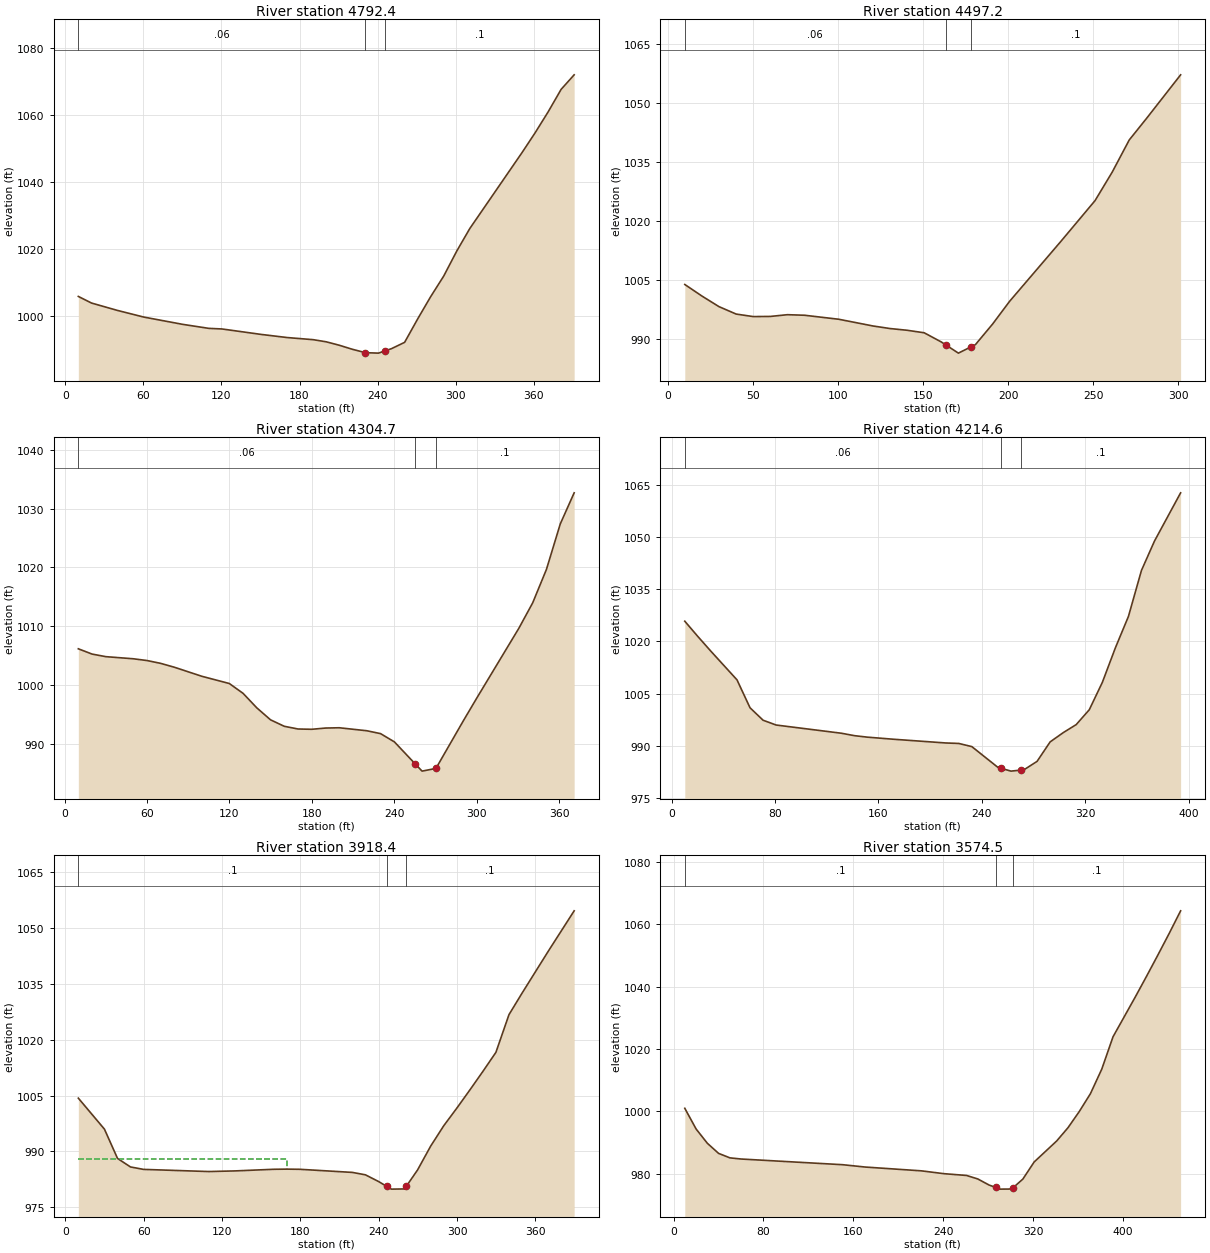
Type RM Length L Ch R = 1 ,4792.4  ,303.6,295.2,286.7
XS GIS Cut Line= 2
     1706403.167      237369.635     1706170.966      237054.874
#Sta/Elev= 28
      10 1005.78    20.1 1003.81    40.1  1001.6    60.2  999.63    90.3  997.44
   110.3  996.25   120.4  996.07   150.4  994.45   170.5  993.51   190.6  992.87
   200.6  992.23   210.6  991.21   220.6  990.01   230.7  988.99   240.7  988.86
   245.7 989.527   250.7  990.19   260.8  992.08   270.8  999.05   280.8  1005.7
   290.8 1011.83   300.9 1019.34   310.9 1026.05     351 1048.68   361.1 1054.61
   371.1 1060.85   381.1 1067.58   391.1 1071.91
#Mann= 3 , 0 , 0
      10     .06       0   230.7    .045       0   245.7      .1       0
Bank Sta=230.7,245.7
XS Rating Curve= 0 ,0
Exp/Cntr=0.3,0.1

Type RM Length L Ch R = 1 ,4497.2  ,198.5,192.5,186.4
XS GIS Cut Line= 2
     1706580.346      237032.019     1706324.925      236872.058
#Sta/Elev= 26
      10 1003.76    20.1 1000.81    30.1  998.12    40.2  996.23    50.2  995.59
    60.3  995.63    70.3  996.07    80.4  995.93   100.5  994.91   120.6   993.2
   130.6  992.55   140.6  992.11   150.7  991.47   160.7  989.14   163.3  988.41
   170.8  986.29   178.3  987.91   180.8  988.45   190.9  993.69   200.9  999.48
   231.1 1014.77   251.1  1025.1   261.2 1032.36   271.2 1040.54   281.3 1045.99
   301.4 1057.12
#Mann= 3 , 0 , 0
      10     .06       0   163.3    .045       0   178.3      .1       0
Bank Sta=163.3,178.3
XS Rating Curve= 0 ,0
Exp/Cntr=0.3,0.1

Type RM Length L Ch R = 1 ,4304.7  ,96.9,90.1,83.4
XS GIS Cut Line= 3
     1706666.328      236955.543     1706568.288      236781.393
     1706404.457      236732.372
#Sta/Elev= 30
      10 1006.16      20 1005.26      30 1004.82      50 1004.46      60 1004.16
    69.9 1003.68    79.9 1003.02    99.9 1001.48   119.9 1000.25   129.9  998.58
   139.9  996.11   149.9  994.07   159.9  992.97   169.9  992.51   179.9  992.46
   189.9  992.67   199.9  992.72     220  992.21     230  991.72   240.1  990.31
   255.3 986.542   260.2  985.34   270.3   985.8   290.4  993.97   300.4  997.92
   330.6 1009.63   340.7 1013.97   350.7 1019.65   360.8 1027.41   370.9  1032.7
#Mann= 3 , 0 , 0
      10     .06       0   255.3    .045       0   270.3      .1       0
Bank Sta=255.3,270.3
XS Rating Curve= 0 ,0
Exp/Cntr=0.3,0.1

Type RM Length L Ch R = 1 ,4214.6  ,300.5,296.2,291.9
XS GIS Cut Line= 2
     1706779.545      236670.171     1706385.655      236673.782
#Sta/Elev= 30
    10.1 1025.82    20.2 1021.43    30.3 1017.19    50.5 1008.96    60.6 1000.92
    70.7  997.34    80.8  995.96   131.3   993.6   141.4   992.9   151.5  992.47
   171.7  991.87   212.1   990.8   222.2  990.66   232.3  989.75   252.5  983.77
   255.1   983.5   262.6   982.7   270.1  982.99   272.7   983.1   282.8  985.51
   292.9  991.11     303  993.76   313.1  996.09   323.2 1000.36   333.3 1008.22
   343.4 1018.17   353.5 1027.19   363.6 1040.45   373.7  1048.9   393.9 1062.75
#Mann= 3 , 0 , 0
    10.1     .06       0   255.1    .045       0   270.1      .1       0
Bank Sta=255.1,270.1
XS Rating Curve= 0 ,0
Exp/Cntr=0.3,0.1

Type RM Length L Ch R = 1 ,3918.4  ,339.4,343.9,348.4
XS GIS Cut Line= 2
     1706726.958      236329.891     1706345.117      236407.291
#Sta/Elev= 28
      10 1004.32      30  995.99      40  988.14    49.9  985.85    59.9  985.19
   109.9  984.61   129.9  984.78   159.8  985.22   169.8  985.26   179.8  985.21
   219.8  984.38   229.8  983.73   239.8  981.94     246  980.66   249.7  979.89
   259.7  979.94     261 980.602   269.7  985.03   279.7  991.41   289.7  996.88
   299.7  1001.6   309.7 1006.49   319.7 1011.48   329.7 1016.62   339.7 1026.74
   349.6 1032.45   369.6 1043.67   389.6 1054.62
#Mann= 3 , 0 , 0
      10      .1       0     246    .045       0     261      .1       0
#XS Ineff= 2 , 0
       0   169.8     988               0
Permanent Ineff=
       F       F
Bank Sta=246,261
XS Rating Curve= 0 ,0
Exp/Cntr=0.3,0.1

Type RM Length L Ch R = 1 ,3574.5  ,213.6,213,212.4
XS GIS Cut Line= 2
     1706751.469      236039.639     1706299.967      236039.639
#Sta/Elev= 30
      10 1000.97    20.1  994.32    30.1  989.75    40.1  986.52    50.2  985.08
    60.2  984.71   150.5  982.89   170.6  982.14   220.7  980.92   240.8  980.01
   260.9  979.44   270.9  978.32   280.9  976.38     287 975.583     291  975.06
     301  975.09     302 975.408     311  978.27   321.1  983.77   341.1  990.48
   351.2  994.74   361.2   999.9   371.2 1005.66   381.3 1013.53   391.3 1023.89
   411.4 1036.83   421.4 1043.45   431.4  1050.2   441.5 1057.15   451.5 1064.27
#Mann= 3 , 0 , 0
      10      .1       0     287    .045       0     302      .1       0
Bank Sta=287,302
XS Rating Curve= 0 ,0
Exp/Cntr=0.3,0.1

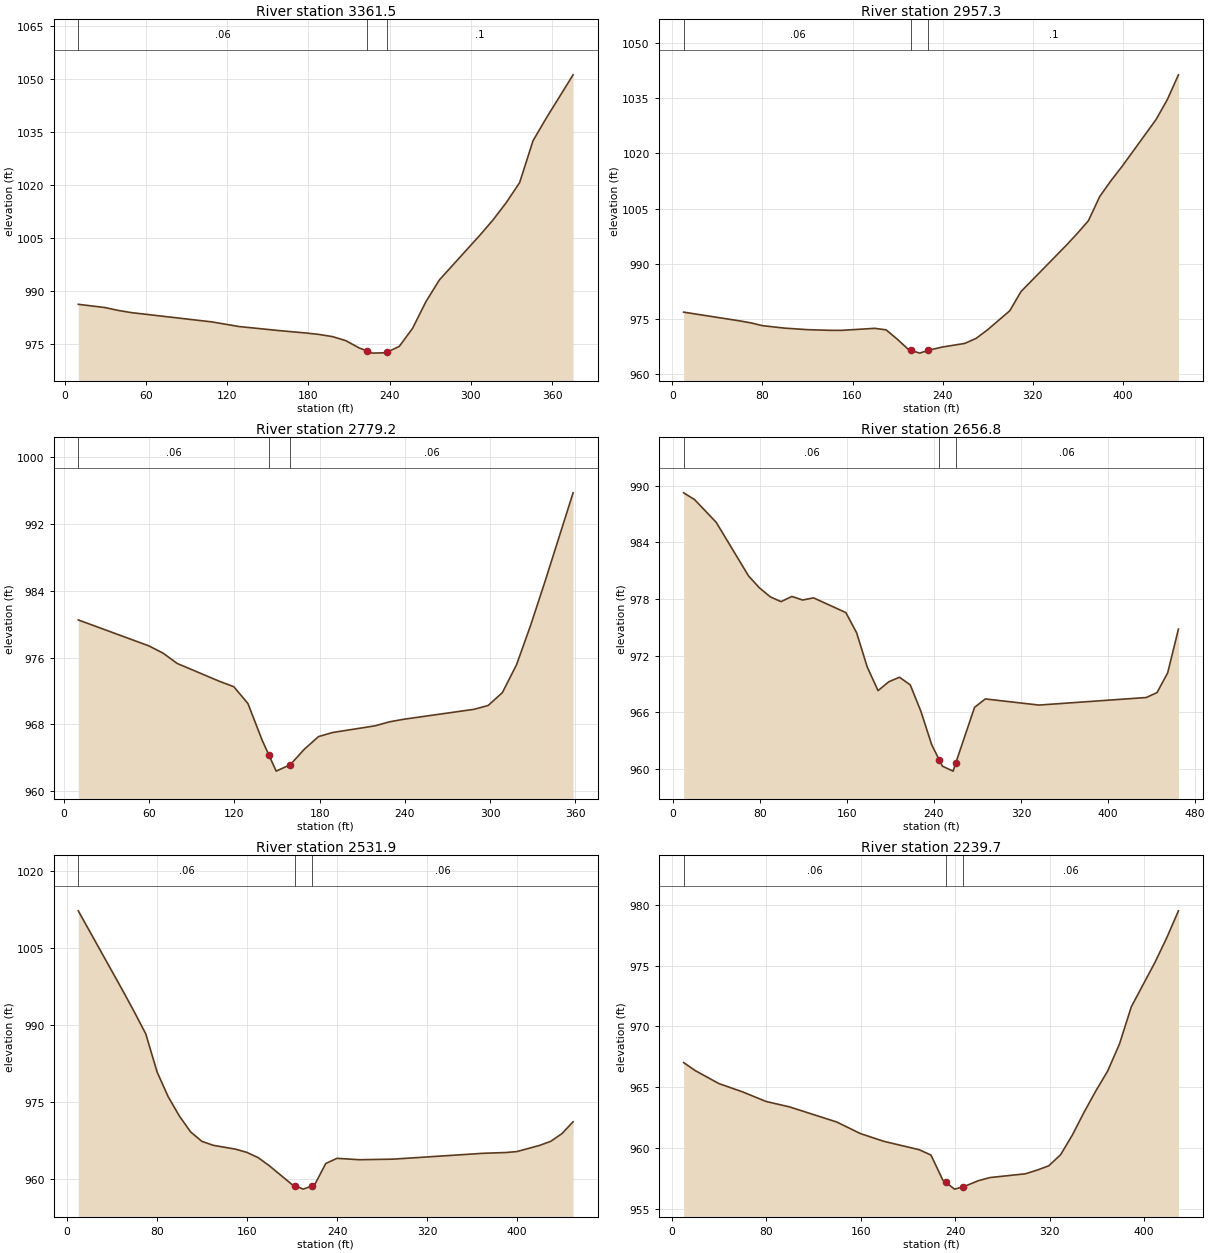
Type RM Length L Ch R = 1 ,3361.5  ,402.9,404.2,405.5
XS GIS Cut Line= 2
     1706689.548      235820.338     1706314.157      235830.658
#Sta/Elev= 27
     9.9  986.12    29.6   985.2    39.5  984.38    49.4  983.75   108.7  981.13
   128.5  979.83   158.1  978.68   177.9     978   187.8  977.58   197.6  976.98
   207.5  975.84   217.4  973.77     223 972.932   227.3  972.29   237.2  972.39
     238 972.537   247.1  974.21   256.9  979.32   266.8  986.89   276.7  993.02
   306.4 1005.59   316.2 1009.95   326.1 1014.91     336 1020.59   345.9 1032.45
   355.8 1038.93   375.5 1051.12
#Mann= 3 , 0 , 0
     9.9     .06       0     223    .045       0     238      .1       0
Bank Sta=223,238
XS Rating Curve= 0 ,0
Exp/Cntr=0.3,0.1

Type RM Length L Ch R = 1 ,2957.3  ,175.5,178.1,180.7
XS GIS Cut Line= 2
     1706694.203      235432.716     1706245.037      235416.995
#Sta/Elev= 30
      10  976.87    59.9  974.49    69.9  973.94    79.9   973.2    99.9  972.52
   119.9  972.11   139.8  971.93   149.8  971.92   179.8  972.47   189.8  972.06
   199.8  969.51   209.7   966.7   212.2  966.46   219.7  965.74   227.2  966.51
   239.7  967.39   259.7  968.38   269.7  969.74   279.7  972.02   299.6  977.23
   309.6  982.46   349.6  994.95   359.6  998.24   369.5 1001.71   379.5 1008.27
   389.5 1012.56   399.5  1016.5   429.5 1029.15   439.5 1034.56   449.4  1041.3
#Mann= 3 , 0 , 0
      10     .06       0   212.2    .045       0   227.2      .1       0
Bank Sta=212.2,227.2
XS Rating Curve= 0 ,0
Exp/Cntr=0.3,0.1

Type RM Length L Ch R = 1 ,2779.2  ,127.2,122.4,117.6
XS GIS Cut Line= 2
     1706672.778      235274.666     1706318.027      235223.066
#Sta/Elev= 24
      10  980.53    59.7  977.42    69.7  976.55    79.7  975.31   109.5  973.17
   119.5  972.53   129.5  970.51   139.4  966.16   144.3 964.321   149.4  962.41
   159.3  963.18   169.3  965.05   179.2  966.55   189.2  967.04   219.1  967.84
     229  968.31     239  968.62   288.8  969.82   298.7  970.28   308.7  971.82
   318.7  975.17   328.6  979.89   338.6  985.07   358.5  995.76
#Mann= 3 , 0 , 0
      10     .06       0   144.3    .045       0   159.3     .06       0
Bank Sta=144.3,159.3
XS Rating Curve= 0 ,0
Exp/Cntr=0.3,0.1

Type RM Length L Ch R = 1 ,2656.8  ,129.4,124.9,120.4
XS GIS Cut Line= 3
     1706750.178      235220.486     1706636.658      235123.735
     1706321.897      235145.665
#Sta/Elev= 30
     9.9  989.25    19.9  988.54    39.8  986.13    69.6  980.44    79.5  979.19
    89.5  978.23    99.4  977.72   109.4  978.27   119.3  977.89   129.3  978.12
     159  976.56   168.9  974.42   178.7  970.78   188.6  968.29   198.5  969.23
   208.3  969.71   218.2   968.9     228  966.09   237.9  962.56     245 960.925
   247.8  960.28   257.6  959.76     260 960.614   277.3  966.52   287.2  967.41
   336.5  966.76   435.1  967.56     445  968.08   454.8  970.17   464.7  974.81
#Mann= 3 , 0 , 0
     9.9     .06       0     245    .045       0     260     .06       0
Bank Sta=245,260
XS Rating Curve= 0 ,0
Exp/Cntr=0.3,0.1

Type RM Length L Ch R = 1 ,2531.9  ,295.4,292.2,289
XS GIS Cut Line= 2
     1706726.006      234950.962     1706292.564      235070.933
#Sta/Elev= 30
      10 1012.23      50   996.5      60  992.45      70  988.25      80  980.86
    89.9  976.01    99.9  972.23   109.9  969.14   119.9  967.31   129.9  966.55
   149.9  965.79   159.9  965.16   169.9  964.14   179.9  962.54   199.9  958.92
   202.4   958.7   209.9  958.01   217.4   958.6   219.9  958.79   229.9     963
   239.9  964.01   259.8  963.74   289.8  963.85   369.8  964.99   389.8  965.14
   399.8  965.33   419.8  966.52   429.8  967.32   439.7  968.81   449.7  971.13
#Mann= 3 , 0 , 0
      10     .06       0   202.4    .045       0   217.4     .06       0
Bank Sta=202.4,217.4
XS Rating Curve= 0 ,0
Exp/Cntr=0.3,0.1

Type RM Length L Ch R = 1 ,2239.7  ,431.1,439.5,447.9
XS GIS Cut Line= 2
     1706616.018      234649.013     1706223.856      234823.164
#Sta/Elev= 30
      10  967.03      20  966.36    39.9   965.3    59.9  964.62    79.8  963.83
    99.8  963.38   139.7  962.14   159.7  961.19   179.6  960.55   209.6  959.86
   219.5  959.42   229.5  957.37     232  957.18   239.5  956.62     247  956.81
   259.5  957.31   269.4  957.57   299.4  957.88   309.3  958.18   319.3  958.54
   329.3  959.45   339.3  961.08   349.3  962.97   359.2  964.71   369.2  966.34
   379.2  968.57   389.2  971.62   409.1  975.25   419.1  977.27   429.1  979.51
#Mann= 3 , 0 , 0
      10     .06       0     232    .045       0     247     .06       0
Bank Sta=232,247
XS Rating Curve= 0 ,0
Exp/Cntr=0.3,0.1

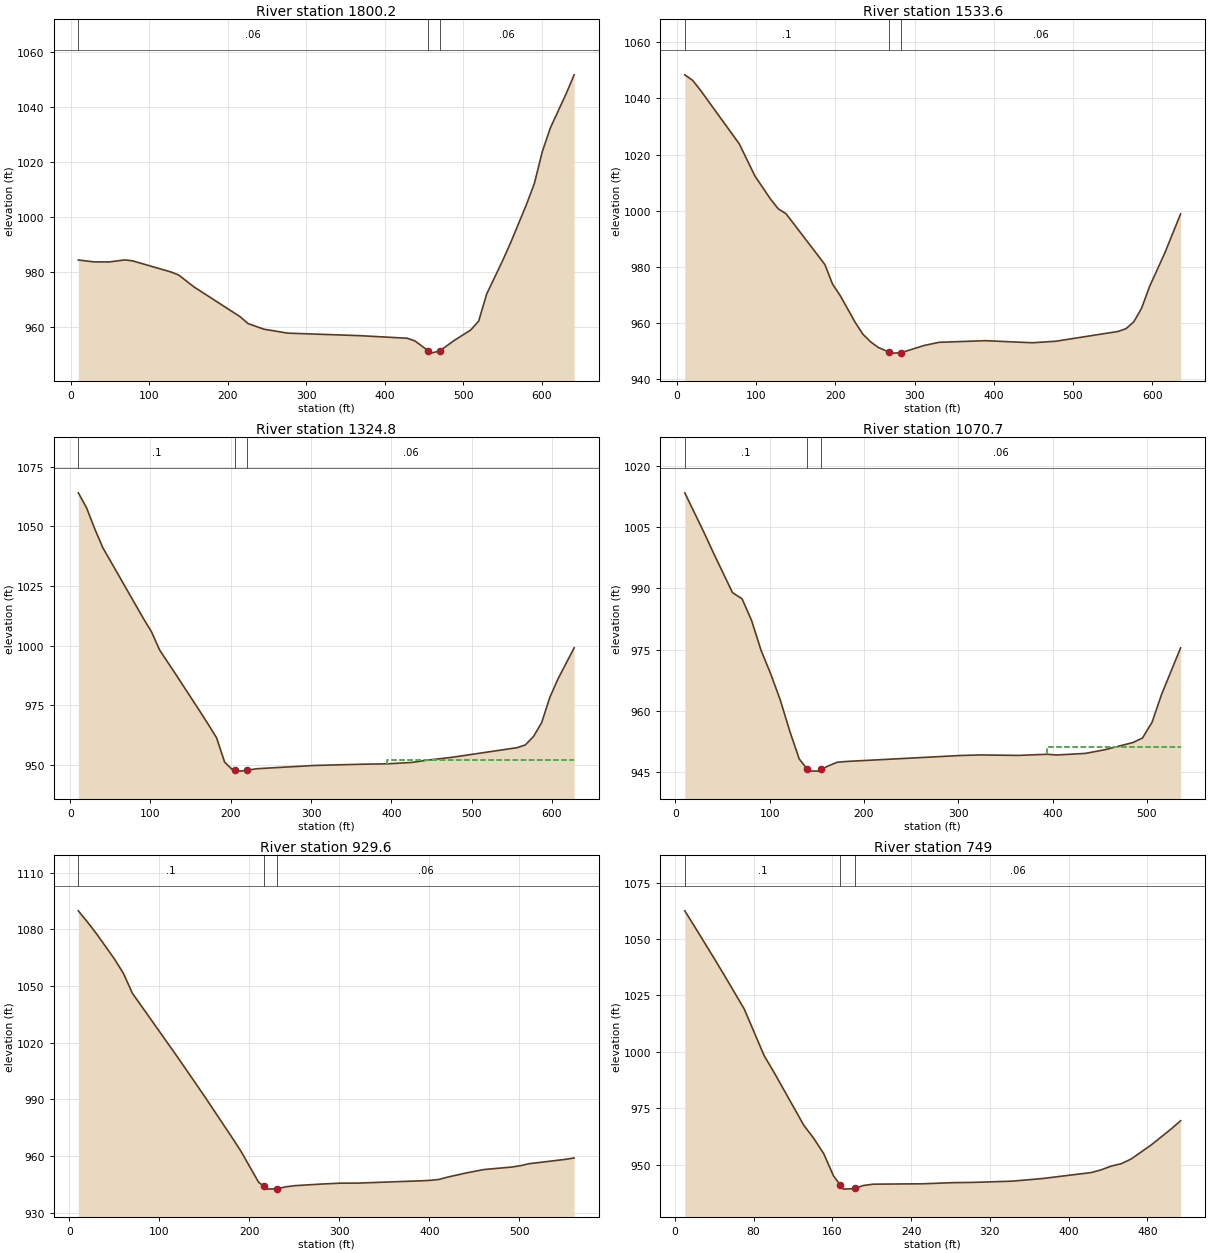
Type RM Length L Ch R = 1 ,1800.2  ,264.9,266.6,268.3
XS GIS Cut Line= 3
     1706743.505      234393.961     1706524.428      234339.056
     1706109.046      234350.666
#Sta/Elev= 30
     9.8  984.36    29.5  983.68    49.1  983.65    68.7  984.38    78.6  984.07
   127.7  980.01   137.5  978.92   157.1  974.57     216  963.72   225.9  961.26
   246.1   959.2   276.5  957.76   367.7  956.85   428.6  955.91   438.7  954.92
     455 951.439     459  950.49     470 951.281   489.4  955.25   509.6  958.89
   519.8  962.17   529.9  971.95   550.2  984.08   560.3  990.53   580.6 1004.51
   590.7 1012.19   600.9 1023.82     611 1032.34   631.3  1044.9   641.4  1051.7
#Mann= 3 , 0 , 0
     9.8     .06       0     455    .045       0     470     .06       0
Bank Sta=455,470
XS Rating Curve= 0 ,0
Exp/Cntr=0.3,0.1

Type RM Length L Ch R = 1 ,1533.6  ,220.2,208.9,197.5
XS GIS Cut Line= 4
     1706635.837      233991.469     1706524.797      234129.472
     1706351.974      234121.555     1706092.105      234240.645
#Sta/Elev= 30
     9.8 1048.38    19.7 1046.43    29.5 1042.94    78.7 1023.77    98.4 1012.35
   118.1 1004.15   127.9 1000.66   137.8  998.91   186.7  980.87   196.4   973.9
     206  969.84   225.2  960.18   234.8  956.04   244.4  953.37     254  951.38
   267.9 949.662   273.2  949.33   282.9  949.47   311.7  952.03   330.9  953.18
   389.6  953.76   448.7  953.02   478.3  953.56   557.1  957.05     567  958.04
   576.8  960.44   586.7  965.31   596.6  972.92   616.3  985.16     636   998.9
#Mann= 3 , 0 , 0
     9.8      .1       0   267.9    .045       0   282.9     .06       0
#XS Ineff= 2 , 0
       0                   389.6       0  953.76
Permanent Ineff=
       F       F
Bank Sta=267.9,282.9
XS Rating Curve= 0 ,0
Exp/Cntr=0.3,0.1

Type RM Length L Ch R = 1 ,1324.8  ,256.8,254.1,251.3
XS GIS Cut Line= 2
      1706587.42       233832.48     1706024.142      234109.909
#Sta/Elev= 30
    10.1 1064.09    20.3 1057.85    30.4 1049.13    40.5 1041.17    91.1 1011.47
   101.3 1005.83   111.4  998.21   131.7  987.94     162   972.3   172.2  966.94
   182.3  961.46   192.4  951.21   202.5   947.9   205.2  947.78   212.7  947.45
   220.2  947.85   232.9  948.47   303.8  949.82   364.6  950.35     395   950.5
   425.3  951.08   445.6  952.07     476  953.26     557  957.29   567.1  958.44
   577.3     962   587.4  967.76   597.5  978.28   607.6  985.99   627.9  999.13
#Mann= 3 , 0 , 0
    10.1      .1       0   205.2    .045       0   220.2     .06       0
#XS Ineff= 2 , 0
       0                     395       0     952
Permanent Ineff=
       F       F
Bank Sta=205.2,220.2
XS Rating Curve= 0 ,0
Exp/Cntr=0.3,0.1

Type RM Length L Ch R = 1 ,1070.7  ,142.2,141.1,140
XS GIS Cut Line= 2
     1706386.536      233630.893     1705938.664      233925.045
#Sta/Elev= 30
    10.1 1013.48    30.3 1003.83    40.4  998.77    60.7  988.97    70.8  987.47
    80.9  982.15      91  974.81   101.1  969.08   111.2  962.73   121.3  955.04
   131.4  948.16     140  945.64   141.5   945.2   151.7  945.16     155 945.565
   161.8   946.4   171.9  947.35     182  947.54   303.3  949.01   323.5  949.13
     364  949.02   394.3   949.3   404.4  949.12   434.7  949.51     455  950.39
   485.3  952.18   495.4   953.3   505.5  957.15   515.6  963.99   535.8  975.42
#Mann= 3 , 0 , 0
    10.1      .1       0     140    .045       0     155     .06       0
#XS Ineff= 2 , 0
       0                   394.3       0     951
Permanent Ineff=
       F       F
Bank Sta=140,155
XS Rating Curve= 0 ,0
Exp/Cntr=0.3,0.1

Type RM Length L Ch R = 1 ,929.6   ,180.7,180.6,180.5
XS GIS Cut Line= 2
     1706359.306      233467.997     1705905.742      233798.207
#Sta/Elev= 30
      10 1089.79      20 1083.97    30.1 1077.72    50.1 1064.31    60.1 1056.65
    70.1 1046.12   120.2 1012.37   150.3  991.51   180.3   970.1   190.4   962.7
   210.4  945.98     216 943.964   220.4  942.38     231 942.575   240.4  943.59
   250.5  944.21   280.5  945.08   300.6  945.53   320.6  945.57   390.7  946.78
   400.7  947.02   410.8  947.51   420.8  948.79   440.8  950.92   460.8  952.76
   490.9  954.04   500.9  954.75   510.9  955.85     551  958.13     561  958.89
#Mann= 3 , 0 , 0
      10      .1       0     216    .045       0     231     .06       0
Bank Sta=216,231
XS Rating Curve= 0 ,0
Exp/Cntr=0.3,0.1

Type RM Length L Ch R = 1 ,749     ,238.4,239.7,240.9
XS GIS Cut Line= 2
     1706210.289      233352.498     1705795.891      233656.481
#Sta/Elev= 30
    10.1 1062.49    20.2 1055.44    40.3 1041.14    50.4 1033.84    70.5 1018.95
    90.7  998.31   100.8  990.84     131  967.42   141.1  961.63   151.2  954.88
   161.2  944.97     168 941.013   171.3  939.09   181.4  939.27     183 939.497
   191.5   940.7   201.5  941.28   251.9  941.46   282.2  941.96   302.3  942.07
   342.6  942.62   372.9  943.76   423.2  946.45   433.3  947.66   443.4   949.3
   453.5  950.35   463.6  952.43   483.7  958.58   503.9  965.62   513.9  969.41
#Mann= 3 , 0 , 0
    10.1      .1       0     168    .045       0     183     .06       0
Bank Sta=168,183
XS Rating Curve= 0 ,0
Exp/Cntr=0.3,0.1

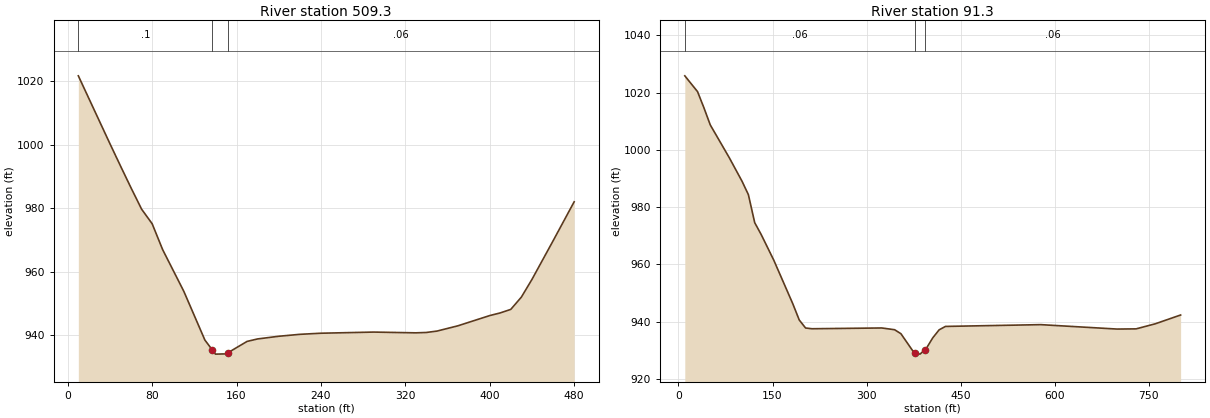
Type RM Length L Ch R = 1 ,509.3   ,412.6,418.1,423.5
XS GIS Cut Line= 2
      1706054.15      233179.651     1705651.825      233441.542
#Sta/Elev= 30
      10 1021.73      40 1000.31      50   993.3      60  986.39      70  979.69
      80   975.1      90   966.9     110  953.81     130  938.43     137 935.328
     140     934     150  934.08     152  934.47     170  938.01     180  938.79
     200  939.63     220  940.24     240  940.59     290  940.95     330  940.71
     340  940.83     350  941.26     370  942.94     400  946.15     410  946.99
     420   948.1     430  951.95     440   957.5   460.1   969.7   480.1  982.02
#Mann= 3 , 0 , 0
      10      .1       0     137    .045       0     152     .06       0
Bank Sta=137,152
XS Rating Curve= 0 ,0
Exp/Cntr=0.3,0.1

Type RM Length L Ch R = 1 ,91.3    ,95,91.3,87.6
XS GIS Cut Line= 2
     1706204.073      232729.882       1705448.1       232993.79
#Sta/Elev= 30
    10.1 1025.85    30.4 1020.34    40.5 1014.76    50.7 1008.72    81.1  997.24
   101.4  989.04   111.5  984.37   121.6  974.58   131.8   970.5     152  961.49
   182.4  946.24   192.6  940.61   202.7  937.82   212.8  937.56   324.3  937.83
   344.6  937.22   354.7  935.83     375   929.4   377.7  929.22   385.2   928.7
   392.7   930.2   395.3  930.72   405.4  934.36   415.6  937.17   425.7  938.37
   577.7  938.99   699.4  937.45   729.8  937.52   760.2  939.28   800.7  942.36
#Mann= 3 , 0 , 0
    10.1     .06       0   377.7    .045       0   392.7     .06       0
Bank Sta=377.7,392.7
XS Rating Curve= 0 ,0
Exp/Cntr=0.3,0.1

Chan Stop Cuts=-1
Use User Specified Reach Order=0